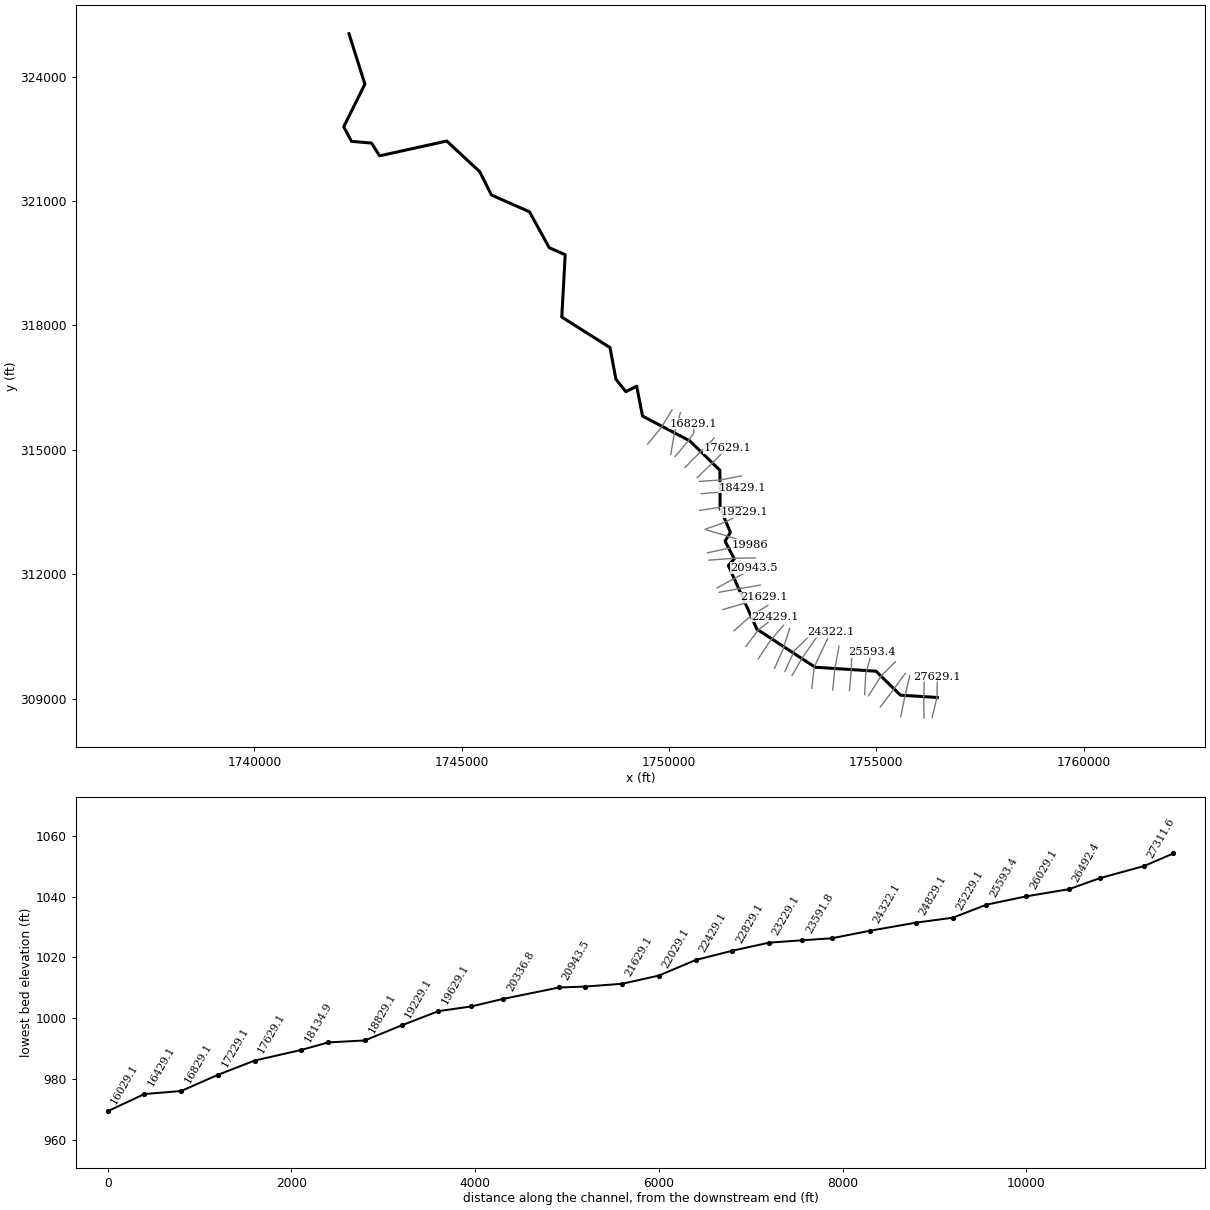
--- ShinsRn.prj (project) ---

Proj Title=ShinsRn
Current Plan=p01
Default Exp/Contr=0,0
English Units
Geom File=g01
Flow File=f01
Plan File=p01
BEGIN DESCRIPTION:
END DESCRIPTION:
DSS Export Rating Curves= 0
DSS Export Rating Curve Sorted= 0
DSS Export Volume Flow Curves= 0
DXF OffsetX= 0
DXF OffsetY= 0
DXF ScaleX= 0
DXF ScaleY= 0

--- ShinsRn.p01 (plan) ---

Plan Title=Floodplain
Program Version=4.00
Geom File=g01
Flow File=f01
K Sum by GR=0
Std Step Tol=0.01
Critical Tol=0.01
Num of Std Step Trials=20
Max Error Tol=0.3
Flow Tol Ratio=0.001
Split Flow NTrial=30
Split Flow Tol=0.02
Split Flow Ratio=0.02
Log Output Level=0
Friction Slope Method=1
Unsteady Friction Slope Method=2
Unsteady Bridges Friction Slope Method=1
Global Log Level=0
CheckData=False
Run HTab=0
Run UNet=0
Run PostProcess=0
UNET Theta=0
UNET Theta Warmup=0
UNET ZTol=0
UNET ZSATol=0
UNET MxIter=0
UNET MaxInSteps=0
UNET DtIC=0
UNET DtMin=0
UNET MaxCRTS=0
UNET WFStab=0
UNET SFStab=0
UNET WFX=0
UNET SFX=0
UNET DSS MLevel=0
UNET DZMax Abort=0
UNET Convert EG Bridges=0
UNET Use Existing IB Tables=0
UNET Froude Limit=0
UNET Froude Power=0
Write IC File=0
Echo Input=False
Echo Output=False
Write Detailed=0

--- ShinsRn.f01 (steady flow) ---

Flow Title=NFF Regression Equation
Program Version=4.00
Number of Profiles= 1
Profile Names=P100yr
River Rch & RM=ShinsRn,Main            ,27629.1
717.7026
River Rch & RM=ShinsRn,Main            ,27311.6
847.6105
River Rch & RM=ShinsRn,Main            ,25593.4
900.3053
River Rch & RM=ShinsRn,Main            ,23908.7
 999.854
River Rch & RM=ShinsRn,Main            ,22029.1
1070.265
River Rch & RM=ShinsRn,Main            ,19229.1
1168.782
River Rch & RM=ShinsRn,Main            ,18829.1
1402.994
River Rch & RM=ShinsRn,Main            ,16829.1
1432.737
River Rch & RM=ShinsRn,Main            ,16429.1
1738.446
River Rch & RM=ShinsRn,Main            ,15318.2
1794.289
River Rch & RM=ShinsRn,Main            ,11329
1983.229
River Rch & RM=ShinsRn,Main            ,6029.1
2192.858
River Rch & RM=ShinsRn,Main            ,29.1
2408.466
River Rch & RM=ShinsRn,Main            ,29.1
2412.229
Boundary for River Rch & Prof#=ShinsRn,Main            , 1
Up Type= 0
Dn Type= 1
Dn Known WS=913.43
DSS Import GetInterval= 0
DSS Import GetPeak= 0
DSS Import FillOption= 0

--- ShinsRn.g01 (geometry) ---

Geom Title=USGS 3m DEM
Program Version=4.00

River Reach=ShinsRn     ,Main
Reach XY= 30
     1756473.384      309025.720     1755583.496      309080.455
     1754993.508      309658.871     1753526.575      309754.920
     1752121.859      310672.011     1751432.035      312208.409
     1751575.038      312367.096     1751352.675      312796.231
     1751482.232      313008.086     1751233.586      313596.546
     1751228.563      314505.658     1750504.317      315212.305
     1749362.608      315812.274     1749221.991      316532.507
     1748960.558      316400.530     1748719.858      316702.342
     1748578.677      317464.165     1747415.125      318199.900
     1747498.111      319703.183     1747112.407      319873.134
     1746636.003      320738.912     1745718.984      321143.424
     1745438.872      321702.501     1744640.043      322445.288
     1743020.450      322088.052     1742826.344      322396.486
     1742343.947      322438.035     1742156.215      322789.527
     1742666.852      323816.514     1742283.457      325032.518

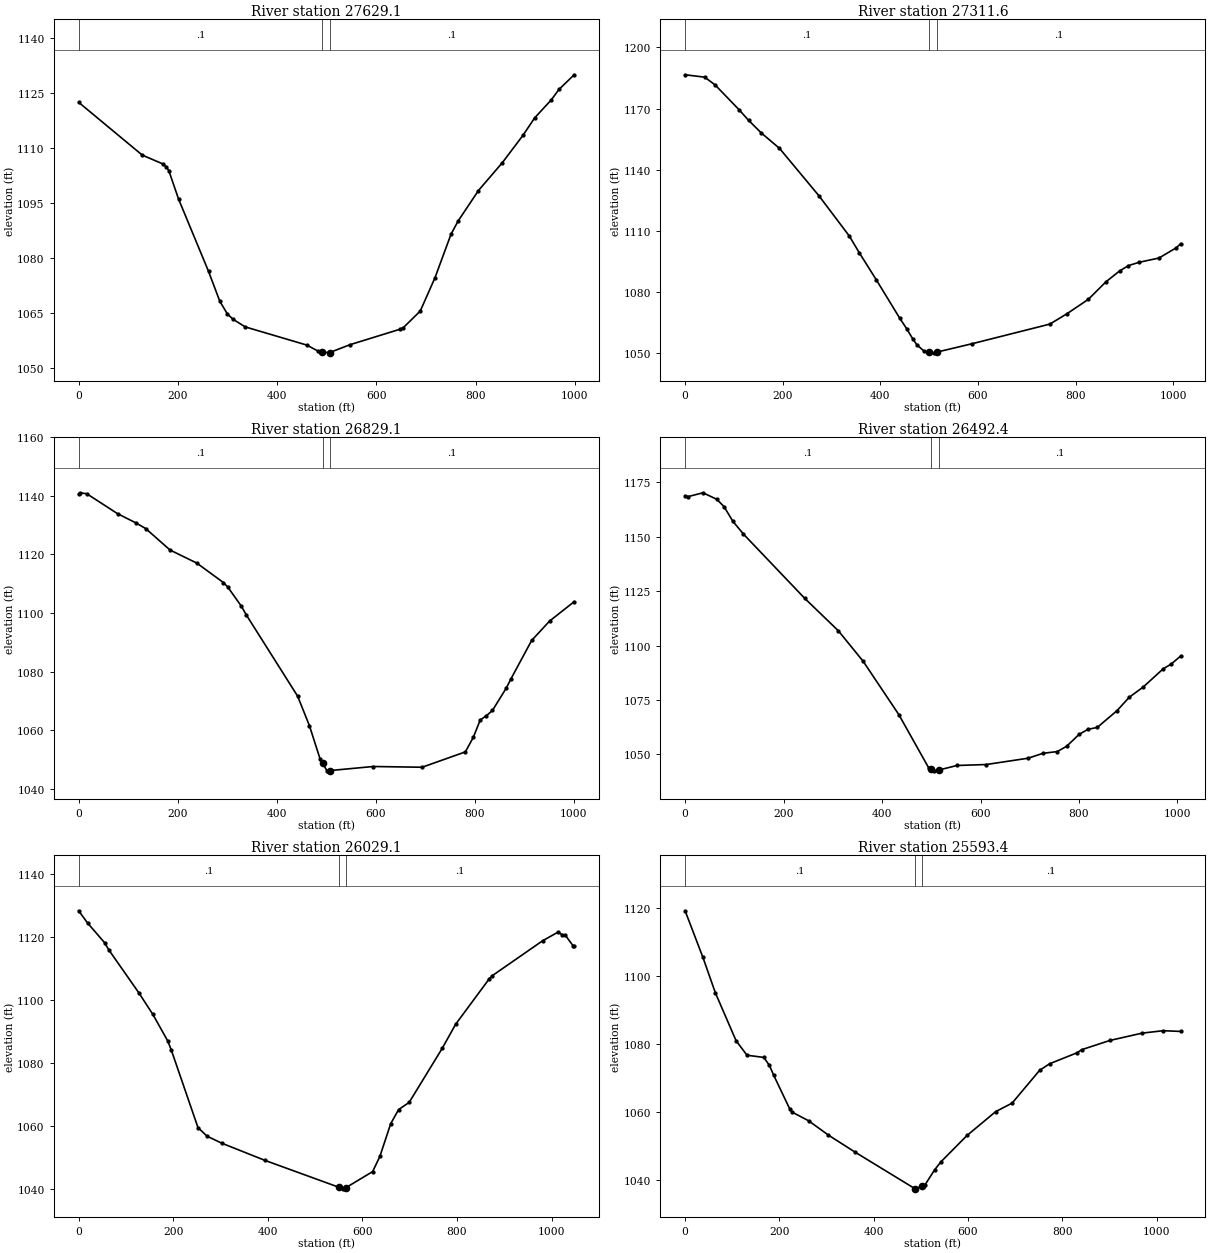
Type RM Length L Ch R = 1 ,27629.1,311.996,317.517,317.644
XS GIS Cut Line= 3
     1756348.134      308541.311     1756463.386      309025.911
     1756472.955      309526.320
#Sta/Elev= 30
       0 1122.42   128.2 1108.05   170.8 1105.59   177.0 1104.78   181.8 1103.81
   201.4 1096.08   261.8 1076.40   284.6 1068.25   299.7 1064.82   311.3 1063.36
   335.7 1061.30   460.1 1056.34   482.3 1054.72   490.6 1054.54   504.2 1054.24
   505.6 1054.31   546.5 1056.44   647.5 1060.66   654.4 1061.10   688.4 1065.61
   718.0 1074.64   750.5 1086.55   765.0 1090.17   805.7 1098.41   853.6 1105.95
   895.5 1113.44   918.8 1118.15   952.4 1123.07   968.1 1125.94   998.6 1129.91
#Mann= 3 , 0 , 0
       0     0.1       0   490.6   0.045       0   505.6     0.1       0
Bank Sta=   490.6,   505.6
Exp/Cntr=0.3,0.1

Type RM Length L Ch R = 1 ,27311.6,488.23,482.483,480.04
XS GIS Cut Line= 3
     1756150.555      308531.560     1756146.182      309048.443
     1756160.147      309546.554
#Sta/Elev= 30
       0 1186.60    40.0 1185.44    61.4 1181.65   110.7 1169.41   130.3 1164.17
   156.3 1158.00   193.3 1150.50   274.2 1127.20   336.3 1107.48   357.0 1099.17
   391.6 1085.99   439.3 1067.27   453.8 1061.99   466.9 1056.76   474.9 1054.06
   489.5 1050.93   500.4 1050.31   509.6 1050.10   515.4 1050.44   588.2 1054.59
   747.3 1064.21   781.7 1069.20   826.1 1076.36   862.3 1084.99   890.0 1090.27
   908.3 1092.92   930.1 1094.55   970.7 1096.63  1006.0 1101.63  1015.2 1103.67
#Mann= 3 , 0 , 0
       0     0.1       0   500.4   0.045       0   515.4     0.1       0
Bank Sta=   500.4,   515.4
Exp/Cntr=0.3,0.1

Type RM Length L Ch R = 1 ,26829.1,347.092,336.709,327.271
XS GIS Cut Line= 3
     1755591.292      308568.219     1755691.806      309058.535
     1755807.788      309545.539
#Sta/Elev= 30
       0 1140.56     3.2 1141.03    16.5 1140.69    78.6 1133.90   116.3 1130.69
   135.6 1128.80   184.7 1121.48   238.7 1117.03   292.4 1110.39   301.1 1108.90
   328.6 1102.34   338.9 1099.29   442.5 1071.57   466.2 1061.54   487.7 1050.20
     493 1048.67   501.7 1046.10     508 1046.20   595.0 1047.58   693.9 1047.33
   781.2 1052.56   797.4 1057.55   811.3 1063.47   823.9 1064.93   836.0 1066.72
   864.1 1074.40   873.7 1077.60   915.2 1090.61   951.4 1097.23  1001.1 1103.85
#Mann= 3 , 0 , 0
       0     0.1       0     493   0.045       0     508     0.1       0
Bank Sta=     493,     508
Exp/Cntr=0.3,0.1

Type RM Length L Ch R = 1 ,26492.4,461.365,463.291,459.95
XS GIS Cut Line= 3
     1755097.555      308796.947     1755404.111      309203.675
     1755698.792      309604.023
#Sta/Elev= 30
       0 1168.84     6.5 1168.52    36.3 1170.25    64.4 1167.25    79.3 1163.82
    96.7 1157.24   118.6 1151.24   243.1 1121.70   311.4 1106.79   361.8 1092.75
   434.0 1068.33   494.8 1043.79   499.9 1043.18   505.9 1042.46   514.9 1042.81
   552.1 1044.92   611.5 1045.36   696.8 1048.27   726.8 1050.52   755.8 1051.31
   775.0 1053.77   800.0 1059.18   818.1 1061.54   837.1 1062.41   877.4 1070.16
   901.8 1076.23   930.5 1081.00   971.2 1089.39   986.9 1091.48  1006.4 1095.20
#Mann= 3 , 0 , 0
       0     0.1       0   499.9   0.045       0   514.9     0.1       0
Bank Sta=   499.9,   514.9
Exp/Cntr=0.3,0.1

Type RM Length L Ch R = 1 ,26029.1,422.857,435.751,448.714
XS GIS Cut Line= 3
     1754812.026      309063.681     1755110.080      309534.797
     1755456.578      309881.914
#Sta/Elev= 30
       0 1128.40    19.0 1124.50    55.1 1118.23    63.3 1116.10   127.6 1102.29
   157.1 1095.47   188.6 1087.01   196.3 1084.04   252.4 1059.55   271.7 1056.82
   302.9 1054.59   394.1 1049.14     550 1040.63   559.7 1040.11     565 1040.46
   621.7 1045.58   637.0 1050.40   659.9 1060.78   676.6 1065.27   699.0 1067.56
   768.9 1084.73   797.2 1092.36   867.6 1106.65   874.6 1107.78   981.2 1118.88
  1014.2 1121.65  1023.2 1120.72  1028.4 1120.81  1045.9 1117.22  1047.9 1117.16
#Mann= 3 , 0 , 0
       0     0.1       0     550   0.045       0     565     0.1       0
Bank Sta=     550,     565
Exp/Cntr=0.3,0.1

Type RM Length L Ch R = 1 ,25593.4,365.221,364.249,369.917
XS GIS Cut Line= 3
     1754719.146      309093.025     1754744.842      309587.474
     1754893.410      310122.937
#Sta/Elev= 30
       0 1119.17    37.7 1105.49    64.1 1095.06   108.0 1080.97   131.2 1076.67
   166.9 1076.02   178.8 1073.67   187.7 1070.83   221.6 1060.95   226.3 1059.98
   262.0 1057.37   303.8 1053.17   359.4 1048.24   487.2 1037.41   487.9 1037.35
   502.2 1038.12   508.6 1038.49   528.9 1042.90   542.5 1045.30   598.2 1053.10
   658.6 1060.07   693.4 1062.57   751.7 1072.21   772.9 1074.15   830.7 1077.36
   841.5 1078.32   900.9 1081.02   969.3 1083.17  1013.5 1083.88  1050.8 1083.67
#Mann= 3 , 0 , 0
       0     0.1       0   487.2   0.045       0   502.2     0.1       0
Bank Sta=   487.2,   502.2
Exp/Cntr=0.3,0.1

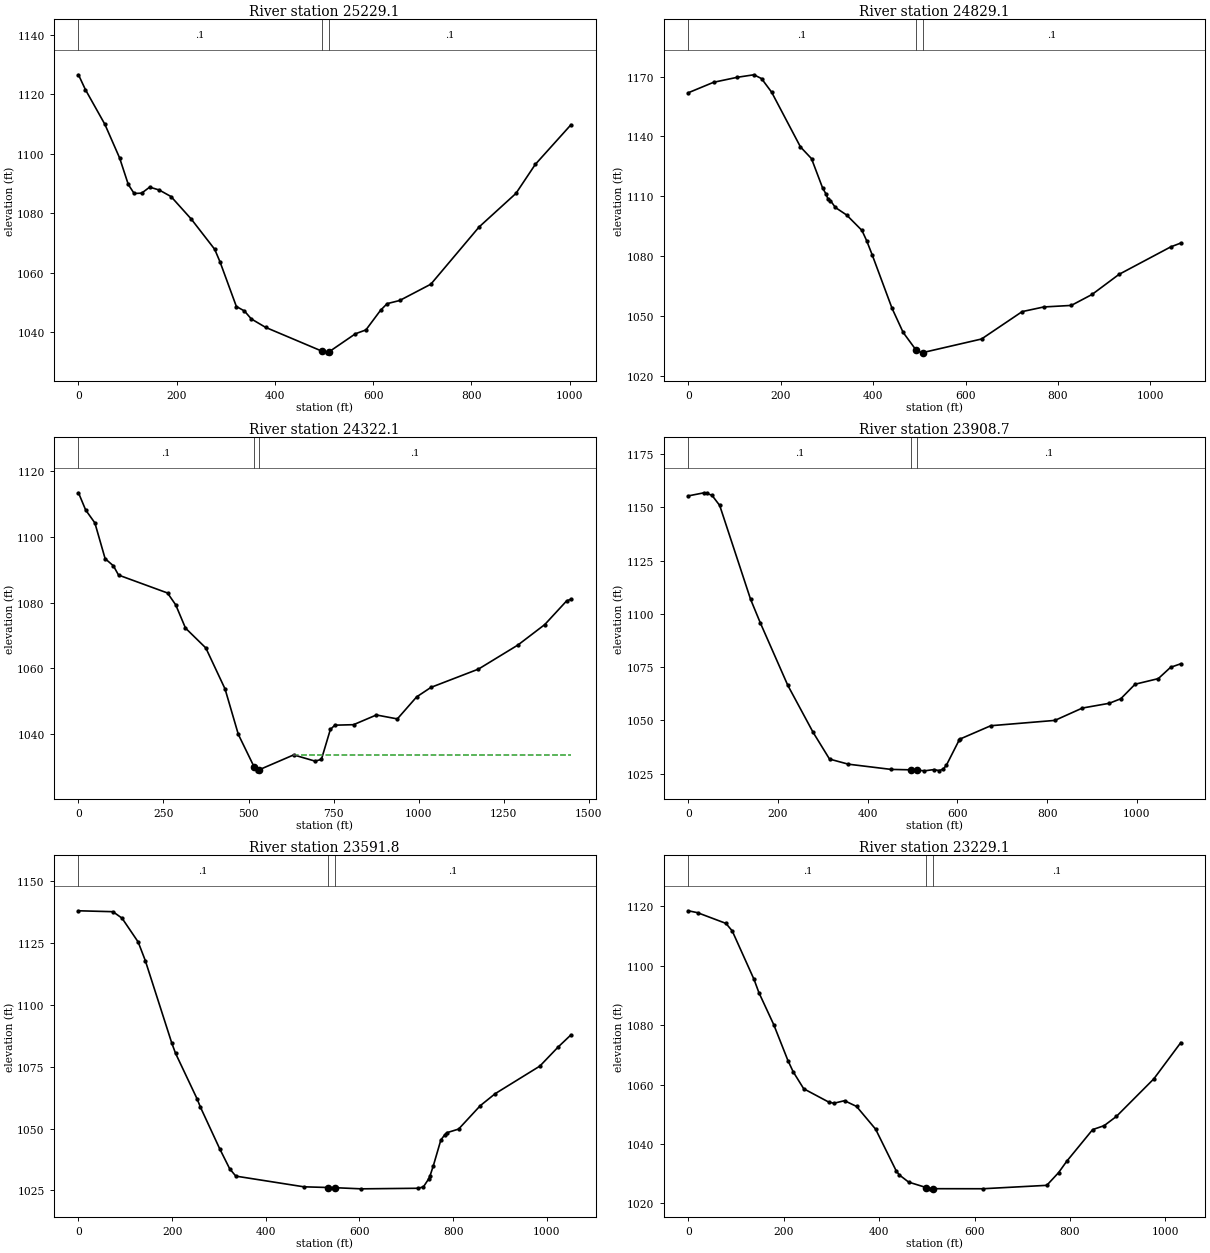
Type RM Length L Ch R = 1 ,25229.1,400.111,400,396.326
XS GIS Cut Line= 3
     1754352.777      309194.348     1754399.652      309694.464
     1754407.866      310194.578
#Sta/Elev= 30
       0 1126.62    14.1 1121.63    53.7 1109.96    83.7 1098.65   101.4 1089.71
   113.3 1086.68   128.7 1086.80   144.9 1088.82   164.4 1087.85   188.4 1085.65
   229.6 1078.07   277.3 1067.90   288.1 1063.68   321.4 1048.66   337.7 1047.17
   351.8 1044.48   380.8 1041.65   494.8 1033.69   506.8 1033.07   509.8 1033.38
   563.8 1039.49   585.1 1040.78   614.9 1047.39   628.3 1049.62   653.8 1050.68
   717.3 1056.17   815.5 1075.42   890.5 1086.71   929.9 1096.47  1002.5 1109.81
#Mann= 3 , 0 , 0
       0     0.1       0   494.8   0.045       0   509.8     0.1       0
Bank Sta=   494.8,   509.8
Exp/Cntr=0.3,0.1

Type RM Length L Ch R = 1 ,24829.1,507.234,507.01,501.074
XS GIS Cut Line= 3
     1753951.165      309208.094     1754000.277      309706.146
     1754101.049      310262.219
#Sta/Elev= 30
       0 1161.86    54.8 1167.11   106.4 1169.63   142.0 1170.87   158.5 1168.95
   180.3 1162.14   242.7 1134.69   266.6 1128.82   290.4 1114.23   297.6 1111.22
   302.4 1108.48   307.5 1107.81   318.2 1104.33   342.6 1100.55   375.7 1092.83
   385.9 1087.68   398.2 1080.38   440.9 1053.74   464.9 1041.66     493 1032.78
   505.2 1031.44     508 1031.60   634.4 1038.37   722.4 1052.12   769.1 1054.44
   828.7 1055.22   873.5 1060.70   931.9 1070.78  1043.9 1084.58  1065.6 1086.49
#Mann= 3 , 0 , 0
       0     0.1       0     493   0.045       0     508     0.1       0
Bank Sta=     493,     508
Exp/Cntr=0.3,0.1

Type RM Length L Ch R = 1 ,24322.1,398.297,413.447,408.061
XS GIS Cut Line= 3
     1753444.742      309243.766     1753503.684      309763.899
     1753899.864      310599.591
#Sta/Elev= 30
       0 1113.41    21.1 1108.17    48.2 1104.24    78.4 1093.34   102.6 1091.18
   117.9 1088.35   261.8 1082.90   286.0 1079.28   314.7 1072.21   374.5 1066.16
   431.0 1053.69   470.1 1039.84     516 1030.07   525.5 1028.75     531 1029.06
   632.8 1033.60   695.7 1031.71   714.4 1032.23   740.7 1041.34   753.8 1042.65
   808.9 1042.80   876.1 1045.76   937.7 1044.56   994.5 1051.27  1036.6 1054.16
  1176.3 1059.73  1292.5 1067.07  1371.3 1073.29  1435.5 1080.49  1448.3 1081.01
#Mann= 3 , 0 , 0
       0     0.1       0     516   0.045       0     531     0.1       0
#XS Ineff= 2 , 0
                          630.65         1033.71
Permanent Ineff=
       F       F
Bank Sta=     516,     531
Exp/Cntr=0.3,0.1

Type RM Length L Ch R = 1 ,23908.7,332.005,316.871,309.138
XS GIS Cut Line= 3
     1752967.436      309557.050     1753219.488      309987.589
     1753562.492      310478.880
#Sta/Elev= 30
       0 1155.36    35.3 1156.82    40.6 1156.51    52.6 1155.69    70.0 1150.87
   138.8 1106.83   160.5 1095.76   221.9 1066.38   278.2 1044.36   314.8 1031.81
   356.6 1029.41   452.2 1026.95   495.6 1026.76   510.6 1026.60   526.4 1026.28
   547.3 1026.86   559.3 1026.41   568.1 1027.06   575.4 1028.94   603.4 1040.55
   606.1 1041.24   674.3 1047.46   817.2 1049.96   878.5 1055.76   938.6 1058.00
   964.2 1060.14   996.0 1066.94  1047.7 1069.57  1075.1 1074.87  1097.9 1076.55
#Mann= 3 , 0 , 0
       0     0.1       0   495.6   0.045       0   510.6     0.1       0
Bank Sta=   495.6,   510.6
Exp/Cntr=0.3,0.1

Type RM Length L Ch R = 1 ,23591.8,365.555,362.672,355.713
XS GIS Cut Line= 3
     1752797.957      309653.832     1753021.618      310150.880
     1753384.334      310504.285
#Sta/Elev= 30
       0 1138.15    73.5 1137.78    93.0 1135.16   127.4 1125.53   142.6 1118.03
   199.2 1084.62   207.2 1080.50   253.1 1062.10   260.5 1058.64   301.3 1041.94
   322.9 1033.74   335.9 1030.79   481.2 1026.46   532.9 1026.18   547.9 1026.10
   603.9 1025.64   725.4 1025.87   736.5 1026.45   748.1 1029.78   750.6 1030.91
   757.8 1035.08   773.7 1045.41   782.1 1047.54   786.2 1048.33   811.6 1049.82
   857.9 1059.30   889.9 1064.17   985.1 1075.31  1024.5 1083.10  1051.5 1087.94
#Mann= 3 , 0 , 0
       0     0.1       0   532.9   0.045       0   547.9     0.1       0
Bank Sta=   532.9,   547.9
Exp/Cntr=0.3,0.1

Type RM Length L Ch R = 1 ,23229.1,399.855,400,391.739
XS GIS Cut Line= 3
     1752545.347      309727.553     1752752.591      310189.551
     1752910.249      310691.244
#Sta/Elev= 30
       0 1118.54    19.3 1117.90    78.9 1114.29    92.1 1111.74   137.8 1095.40
   148.0 1090.95   179.1 1080.16   208.9 1068.04   219.9 1064.27   241.9 1058.57
   294.0 1054.11   305.1 1053.69   327.4 1054.55   352.6 1052.62   392.6 1044.95
   435.9 1030.86   442.5 1029.51   461.8 1027.12   498.9 1025.27   506.3 1024.85
   513.9 1024.90   617.1 1024.88   751.3 1026.03   776.1 1030.32   793.0 1034.11
   847.5 1044.81   871.5 1046.13   897.1 1049.23   975.7 1061.91  1032.2 1074.12
#Mann= 3 , 0 , 0
       0     0.1       0   498.9   0.045       0   513.9     0.1       0
Bank Sta=   498.9,   513.9
Exp/Cntr=0.3,0.1

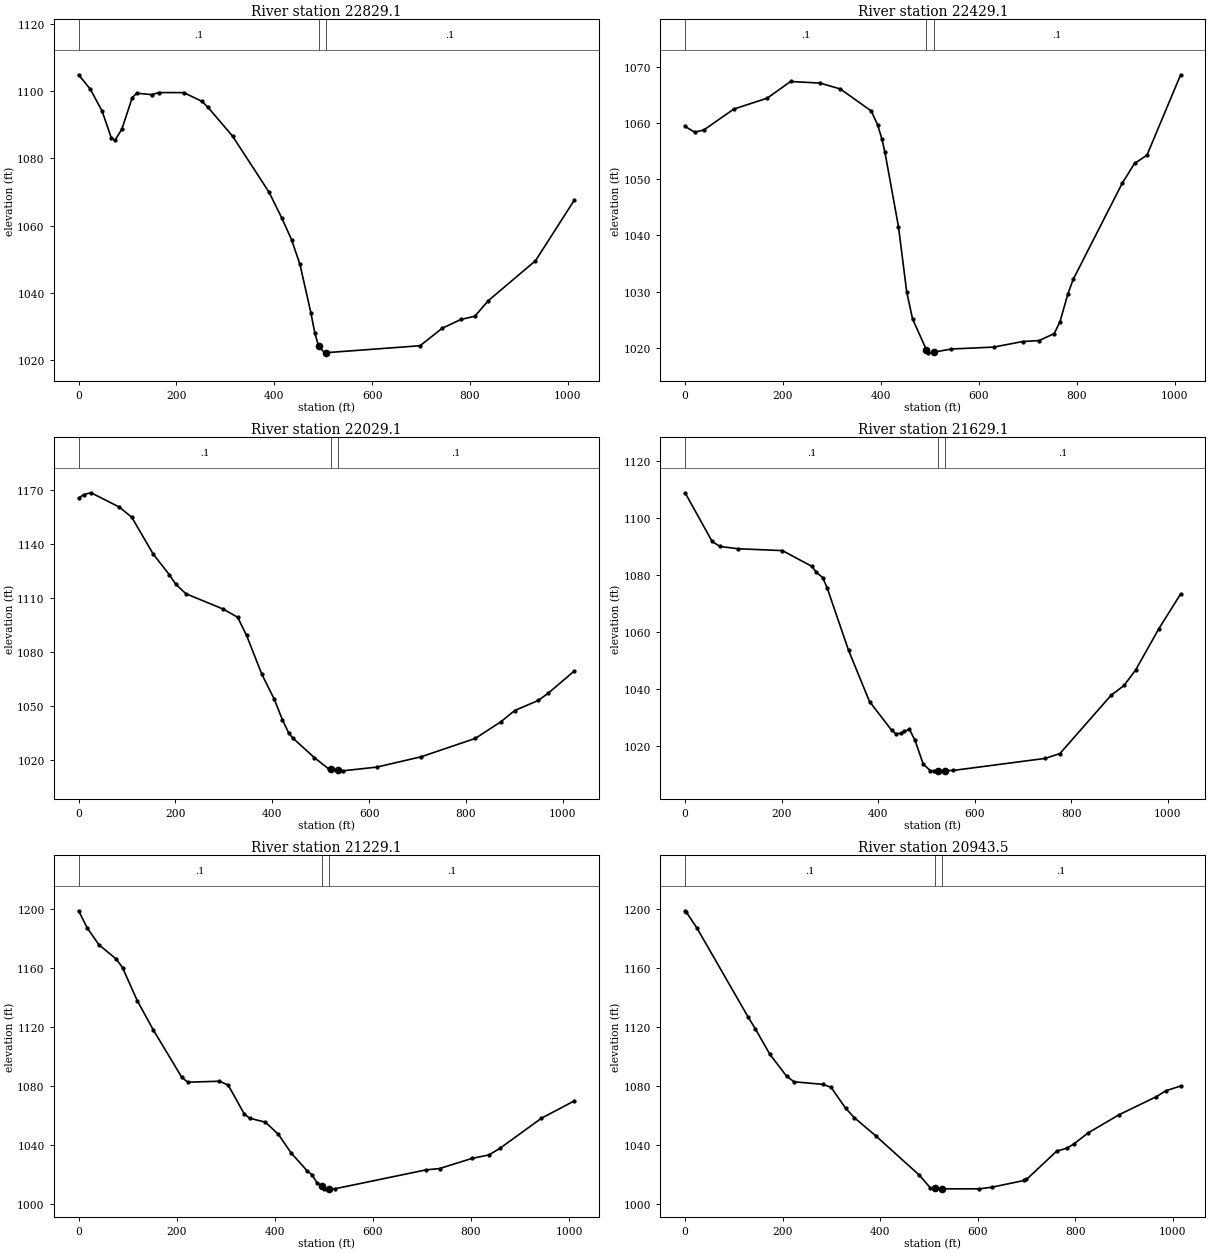
Type RM Length L Ch R = 1 ,22829.1,402.013,400,394.891
XS GIS Cut Line= 3
     1752154.554      309957.646     1752428.389      310373.498
     1752762.809      310765.351
#Sta/Elev= 30
       0 1104.78    23.9 1100.50    48.1 1093.96    66.8 1086.03    74.1 1085.29
    88.3 1088.60   109.6 1097.99   118.8 1099.31   149.7 1098.88   163.6 1099.50
   215.1 1099.48   252.0 1096.90   264.4 1095.13   314.7 1086.56   389.4 1069.88
   415.3 1062.25   435.3 1055.82   452.5 1048.45   474.7 1034.16   482.7 1028.22
   490.4 1024.21   502.8 1022.20   505.4 1022.24   698.1 1024.31   743.2 1029.49
   781.7 1032.12   810.0 1033.06   837.7 1037.72   934.0 1049.55  1013.1 1067.48
#Mann= 3 , 0 , 0
       0     0.1       0   490.4   0.045       0   505.4     0.1       0
Bank Sta=   490.4,   505.4
Exp/Cntr=0.3,0.1

Type RM Length L Ch R = 1 ,22429.1,404.379,400,397.75
XS GIS Cut Line= 3
     1751851.889      310252.768     1752154.605      310650.794
     1752555.697      310968.599
#Sta/Elev= 30
       0 1059.35    19.7 1058.33    38.4 1058.73    99.5 1062.44   167.8 1064.38
   215.4 1067.34   275.9 1067.05   317.1    1066   379.9 1062.11   393.1 1059.65
   401.8 1057.13   408.0 1054.78   435.7 1041.53   452.5 1029.95   464.4 1025.16
   492.6 1019.69   496.8 1019.13   507.6 1019.25   543.8 1019.81   630.0 1020.15
   689.5 1021.14   723.1 1021.31   753.7 1022.56   765.5 1024.67   781.4 1029.55
   792.4 1032.18   892.6 1049.27   917.6 1052.77   943.0 1054.24  1011.8 1068.53
#Mann= 3 , 0 , 0
       0     0.1       0   492.6   0.045       0   507.6     0.1       0
Bank Sta=   492.6,   507.6
Exp/Cntr=0.3,0.1

Type RM Length L Ch R = 1 ,22029.1,407.246,400,394.9
XS GIS Cut Line= 3
     1751569.463      310634.498     1751964.570      310984.579
     1752384.834      311247.379
#Sta/Elev= 30
       0 1165.72    10.6 1167.72    25.8 1168.69    84.4 1160.69   109.9 1155.02
   154.2 1134.53   187.3 1123.15   200.8 1117.77   221.7 1112.52   299.2 1103.93
   328.5 1099.43   346.8 1089.39   378.5 1067.70   404.2 1053.81   421.1 1042.29
   433.8 1035.12   441.9 1032.36   487.0 1021.35   517.1 1014.96   520.4 1014.85
   535.4 1014.34   545.7 1014.01   615.9 1016.09   708.0 1021.87   819.2 1032.03
   872.1 1041.30   900.7 1047.55   949.6 1053.18   969.4 1057.07  1023.6 1069.48
#Mann= 3 , 0 , 0
       0     0.1       0   520.4   0.045       0   535.4     0.1       0
Bank Sta=   520.4,   535.4
Exp/Cntr=0.3,0.1

Type RM Length L Ch R = 1 ,21629.1,404.23,400,396.725
XS GIS Cut Line= 3
     1751299.860      311144.473     1751809.119      311293.984
     1752283.793      311437.975
#Sta/Elev= 30
       0 1108.73    56.0 1091.69    72.2 1089.92   109.8 1089.12   201.6 1088.47
   262.8 1082.94   271.8 1080.92   285.3 1078.98   294.8 1075.20   338.7 1053.53
   382.1 1035.60   427.7 1025.59   436.4 1024.33   447.8 1024.42   452.7 1025.10
   464.9 1025.81   476.5 1021.97   493.5 1013.62   508.3 1011.38   516.7 1011.31
   523.3 1011.32   538.3 1011.35   555.5 1011.45   746.6 1015.68   776.8 1017.38
   882.6 1037.77   909.5 1041.21   933.7 1046.69   981.8 1061.15  1026.8 1073.28
#Mann= 3 , 0 , 0
       0     0.1       0   523.3   0.045       0   538.3     0.1       0
Bank Sta=   523.3,   538.3
Exp/Cntr=0.3,0.1

Type RM Length L Ch R = 1 ,21229.1,278.471,285.664,292.591
XS GIS Cut Line= 3
     1751206.422      311562.076     1751701.497      311650.485
     1752201.618      311735.530
#Sta/Elev= 30
       0 1198.79    17.3 1187.27    41.5 1175.71    76.9 1166.04    89.7 1160.11
   119.4 1137.96   152.5 1117.88   210.3 1085.98   222.4 1082.66   287.1 1083.29
   305.0 1080.68   337.4 1061.22   348.5 1058.24   380.9 1055.54   407.1 1047.37
   432.8 1034.89   465.7 1022.63   475.6 1019.96   486.2 1014.41   495.4 1012.16
   499.8 1010.39   510.4 1010.42   521.7 1010.39   707.7 1023.20   735.9 1024.15
   801.5 1030.97   836.5 1033.39   858.6 1037.79   943.5 1058.23  1010.2 1069.93
#Mann= 3 , 0 , 0
       0     0.1       0   495.4   0.045       0   510.4     0.1       0
Bank Sta=   495.4,   510.4
Exp/Cntr=0.3,0.1

Type RM Length L Ch R = 1 ,20943.5,615.804,606.628,595.789
XS GIS Cut Line= 3
     1751162.269      311668.977     1751618.733      311918.128
     1752058.959      312146.407
#Sta/Elev= 30
       0 1198.50     2.5 1197.60    24.2 1186.87   128.8 1126.73   144.1 1118.46
   173.9 1101.20   208.1 1086.41   223.3 1082.66   282.0 1080.89   299.1 1078.94
   329.2 1064.66   347.2 1058.24   391.7 1045.76   480.2 1019.38   502.6 1010.82
   511.3 1010.65   526.3 1010.29   529.5 1010.09   603.0 1010.10   629.0 1011.19
   695.7 1015.81   699.9 1016.45   761.7 1035.61   783.1 1037.67   798.3 1040.81
   826.0 1047.93   890.3 1060.42   966.0 1072.50   985.6 1076.58  1015.9 1079.76
#Mann= 3 , 0 , 0
       0     0.1       0   511.3   0.045       0   526.3     0.1       0
Bank Sta=   511.3,   526.3
Exp/Cntr=0.3,0.1

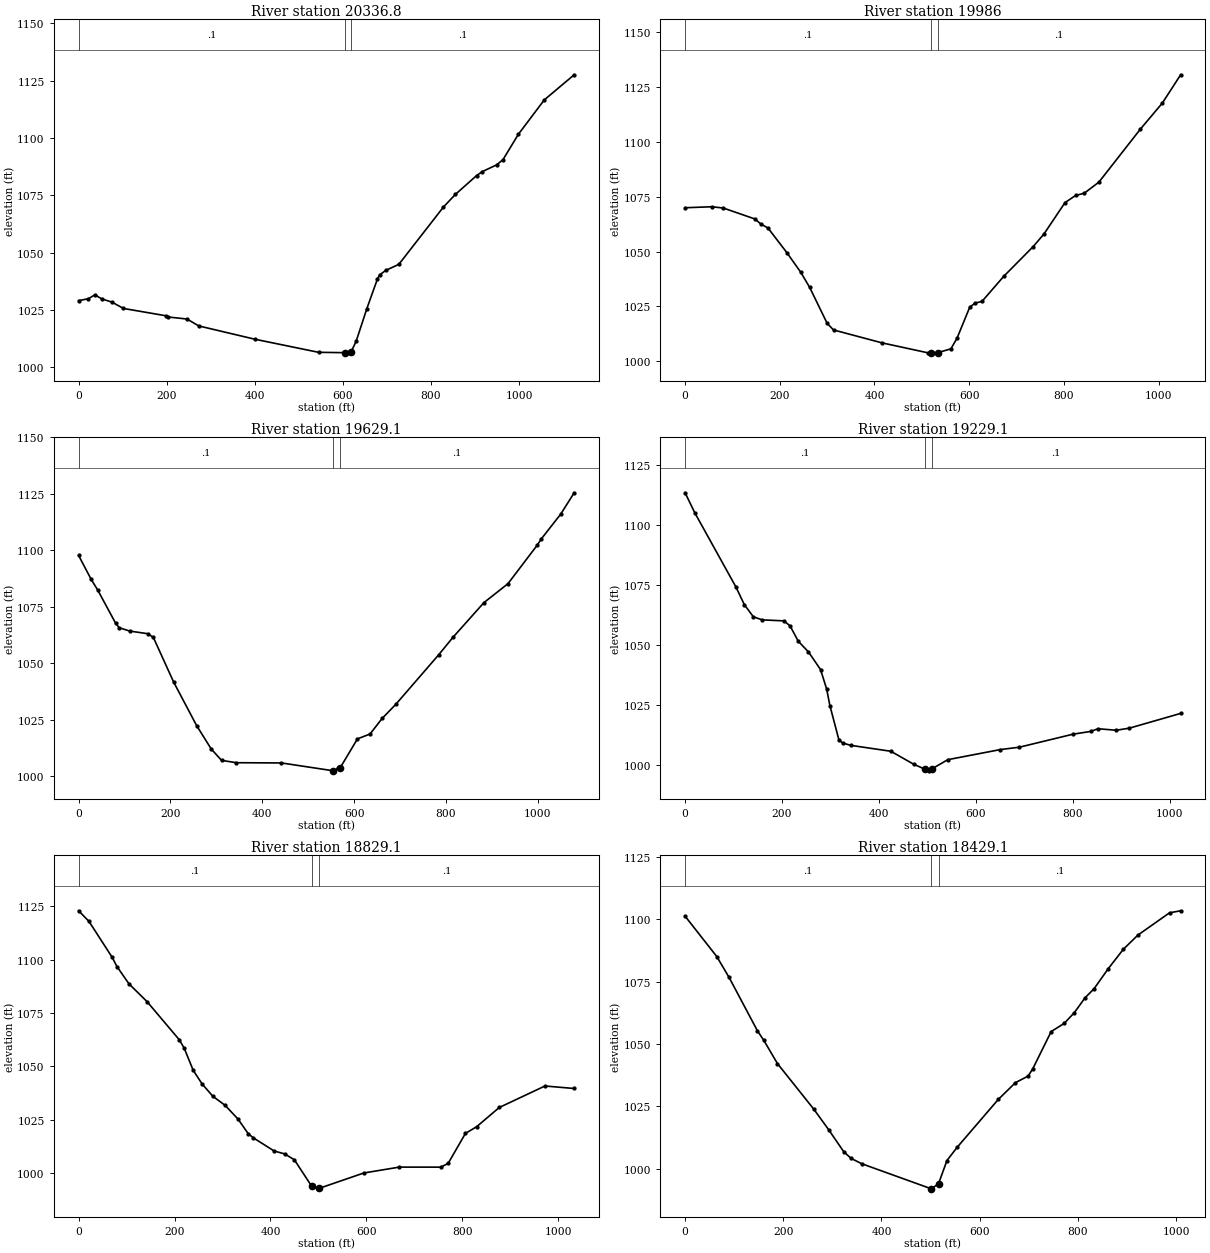
Type RM Length L Ch R = 1 ,20336.8,345.556,350.804,353.499
XS GIS Cut Line= 3
     1750962.543      312336.381     1751575.400      312382.402
     1752086.101      312391.687
#Sta/Elev= 30
       0 1029.10    22.1 1029.95    37.0 1031.64    52.4 1029.87    75.7 1028.46
   101.8 1025.70   199.1 1022.48   203.5 1021.97   246.1 1021.09   272.8 1018.08
   400.6 1012.27   544.9 1006.58   603.9 1006.42   612.9 1006.35   618.9 1006.85
   630.2 1011.36   654.5 1025.59   678.2 1038.32   683.4 1040.30   697.4 1042.27
   727.2 1044.92   828.5 1069.91   855.5 1075.39   903.8 1083.63   917.0 1085.37
   949.2 1088.28   963.7 1090.55   998.8 1101.66  1057.5 1116.60  1125.4 1127.56
#Mann= 3 , 0 , 0
       0     0.1       0   603.9   0.045       0   618.9     0.1       0
Bank Sta=   603.9,   618.9
Exp/Cntr=0.3,0.1

Type RM Length L Ch R = 1 ,19986,366.588,356.904,347.683
XS GIS Cut Line= 3
     1750929.979      312514.875     1751442.309      312623.824
     1751957.674      312711.787
#Sta/Elev= 30
       0 1069.96    56.6 1070.41    80.8 1069.82   147.3 1064.85   160.6 1062.44
   174.9 1060.76   215.1 1049.45   244.1 1040.61   262.8 1033.79   300.1 1017.25
   313.5 1014.27   415.6 1008.40   513.0 1003.84   518.3 1003.85   533.3 1003.92
   561.4 1005.65   574.5 1010.59   601.1 1024.60   612.5 1026.53   627.0 1027.27
   673.3 1038.77   735.3 1052.29   757.9 1057.99   802.4 1072.30   824.7 1075.55
   843.1 1076.58   874.1 1081.66   961.1 1105.66  1008.0 1117.67  1046.6 1130.55
#Mann= 3 , 0 , 0
       0     0.1       0   518.3   0.045       0   533.3     0.1       0
Bank Sta=   518.3,   533.3
Exp/Cntr=0.3,0.1

Type RM Length L Ch R = 1 ,19629.1,387.295,400,417.466
XS GIS Cut Line= 3
     1750913.037      313063.337     1751451.801      312905.201
     1751940.629      312735.250
#Sta/Elev= 30
       0 1097.71    27.4 1087.09    41.7 1082.35    80.6 1067.68    88.5 1065.69
   111.4 1064.22   150.8 1063.05   162.7 1061.41   207.2 1041.50   257.2 1022.24
   288.8 1011.95   311.2 1006.93   343.5 1005.89   441.5 1005.79     554 1002.33
   555.6 1002.29   564.7 1003.41     569 1003.46   607.1 1016.45   634.6 1018.62
   661.0 1025.55   690.3 1031.69   783.7 1053.64   815.0 1061.43   882.4 1076.81
   934.8 1085.21   998.5 1102.27  1007.5 1105.08  1049.8 1116.07  1079.0 1125.50
#Mann= 3 , 0 , 0
       0     0.1       0     554   0.045       0     569     0.1       0
Bank Sta=     554,     569
Exp/Cntr=0.3,0.1

Type RM Length L Ch R = 1 ,19229.1,404.741,400,389.134
XS GIS Cut Line= 3
     1750876.936      313083.431     1751349.682      313251.063
     1751812.326      313490.271
#Sta/Elev= 30
       0 1113.58    19.9 1105.27   104.9 1074.28   122.1 1066.97   140.8 1061.85
   159.3 1060.57   203.9 1060.16   216.5 1058.08   233.6 1051.63   254.3 1047.28
   279.5 1039.84   292.1 1031.68   298.7 1024.86   317.3 1010.55   324.9 1009.23
   341.8 1008.24   424.5 1005.77   471.6 1000.37   494.1  998.36   503.2  997.61
   509.1  998.42   542.1 1002.27   650.5 1006.48   689.7 1007.47   800.6 1012.91
   836.7 1014.04   851.9 1015.17   889.6 1014.54   916.6 1015.41  1022.4 1021.56
#Mann= 3 , 0 , 0
       0     0.1       0   494.1   0.045       0   509.1     0.1       0
Bank Sta=   494.1,   509.1
Exp/Cntr=0.3,0.1

Type RM Length L Ch R = 1 ,18829.1,401.461,400,404.168
XS GIS Cut Line= 3
     1750743.192      313538.788     1751231.503      313610.696
     1751771.154      313619.910
#Sta/Elev= 30
       0 1122.84    21.5 1117.89    69.8 1101.10    79.9 1096.73   105.0 1088.63
   142.8 1080.27   209.5 1062.55   220.0 1058.59   238.9 1048.14   257.5 1041.76
   279.7 1036.02   305.5 1031.73   332.5 1025.28   353.5 1018.52   364.1 1016.55
   407.7 1010.37   429.3 1009.03   449.8 1006.27   486.1  993.82   498.7  992.65
   501.1  992.85   594.7 1000.07   668.6 1002.82   755.3 1002.81   770.6 1004.59
   806.6 1018.62   829.9 1021.73   877.1 1030.74   972.4 1040.80  1033.3 1039.63
#Mann= 3 , 0 , 0
       0     0.1       0   486.1   0.045       0   501.1     0.1       0
Bank Sta=   486.1,   501.1
Exp/Cntr=0.3,0.1

Type RM Length L Ch R = 1 ,18429.1,295.193,294.263,294.016
XS GIS Cut Line= 3
     1750779.801      313939.858     1751286.691      313983.368
     1751777.355      314083.457
#Sta/Elev= 30
       0 1101.19    64.5 1085.04    89.7 1076.64   147.4 1055.27   160.3 1051.48
   188.2 1042.14   262.4 1023.84   292.5 1015.67   323.0 1006.91   338.1 1004.18
   360.3 1002.01   501.3  992.02   501.7  991.99   516.3  994.05   533.4 1003.31
   554.4 1008.67   637.9 1027.78   673.0 1034.53   698.7 1037.13   708.2 1040.05
   745.8 1054.99   772.1 1058.23   792.8 1062.52   814.7 1068.50   833.2 1072.15
   861.9 1080.14   892.6 1087.90   922.5 1093.63   986.9 1102.55  1009.5 1103.36
#Mann= 3 , 0 , 0
       0     0.1       0   501.3   0.045       0   516.3     0.1       0
Bank Sta=   501.3,   516.3
Exp/Cntr=0.3,0.1

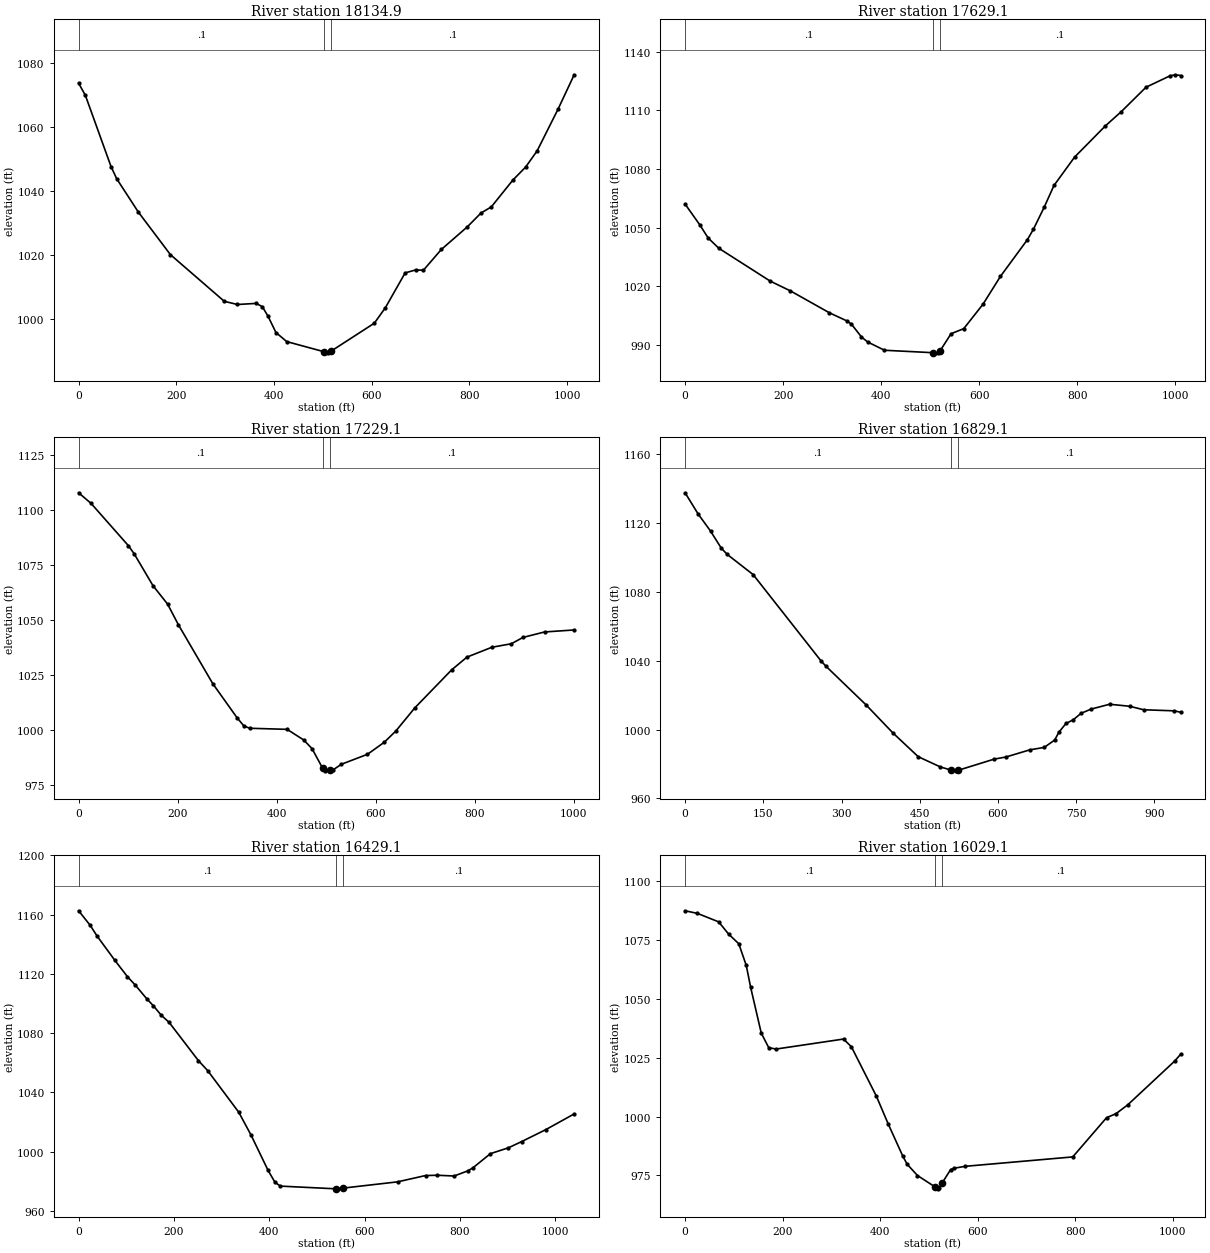
Type RM Length L Ch R = 1 ,18134.9,489.204,505.736,519.339
XS GIS Cut Line= 3
     1750737.317      314237.506     1751247.314      314270.448
     1751740.804      314369.400
#Sta/Elev= 30
       0 1073.72    13.9 1069.88    66.4 1047.65    78.1 1043.83   122.3 1033.45
   187.9 1020.17   298.2 1005.59   325.1 1004.60   363.3 1004.94   376.0 1003.93
   387.6 1000.97   403.9  995.85   426.0  993.01   502.5  989.84   510.6  989.50
   517.5  990.10   605.4  998.77   628.0 1003.61   668.4 1014.47   689.6 1015.38
   705.8 1015.31   742.5 1021.79   795.5 1028.83   823.5 1033.14   844.8 1035.09
   888.8 1043.44   915.0 1047.52   938.6 1052.59   981.1 1065.52  1014.4 1076.35
#Mann= 3 , 0 , 0
       0     0.1       0   502.5   0.045       0   517.5     0.1       0
Bank Sta=   502.5,   517.5
Exp/Cntr=0.3,0.1

Type RM Length L Ch R = 1 ,17629.1,399.553,400,399.904
XS GIS Cut Line= 3
     1750682.326      314329.106     1751051.160      314684.471
     1751402.964      315037.566
#Sta/Elev= 30
       0 1062.06    30.2 1051.36    47.0 1044.74    68.7 1039.48   173.6 1022.68
   214.9 1017.67   294.3 1006.49   330.0 1002.33   339.3 1000.68   359.6  994.16
   372.3  991.57   406.6  987.34   504.7  986.10   515.4  986.02   519.7  986.90
   542.4  995.79   568.3  998.39   607.5 1010.85   643.1 1025.09   697.9 1043.80
   710.3 1049.17   732.2 1060.39   752.3 1071.57   794.3 1086.06   857.2 1102.04
   889.7 1109.34   940.0 1121.79   988.8 1127.60   999.9 1128.15  1010.6 1127.76
#Mann= 3 , 0 , 0
       0     0.1       0   504.7   0.045       0   519.7     0.1       0
Bank Sta=   504.7,   519.7
Exp/Cntr=0.3,0.1

Type RM Length L Ch R = 1 ,17229.1,398.082,400,404.715
XS GIS Cut Line= 3
     1750384.525      314572.673     1750737.558      314927.457
     1751091.907      315280.921
#Sta/Elev= 30
       0 1107.77    25.2 1102.92   100.7 1083.67   112.2 1080.02   150.3 1065.49
   179.8 1057.11   201.7 1047.68   271.1 1020.91   320.4 1005.34   334.1 1001.65
   346.0 1000.67   421.1 1000.18   454.7  995.34   471.5  991.41     493  982.46
   496.7  981.31     508  981.56   513.5  981.68   530.8  984.30   583.5  988.84
   617.2  994.27   640.7  999.40   679.0 1009.92   753.4 1027.21   784.4 1033.03
   834.7 1037.51   874.1 1039.11   897.6 1041.99   941.2 1044.47  1001.0 1045.38
#Mann= 3 , 0 , 0
       0     0.1       0     493   0.045       0     508     0.1       0
Bank Sta=     493,     508
Exp/Cntr=0.3,0.1

Type RM Length L Ch R = 1 ,16829.1,387.954,400,406.44
XS GIS Cut Line= 4
     1750146.511      314833.512     1750479.537      315228.554
     1750604.526      315419.156     1750580.888      315623.516
#Sta/Elev= 30
       0 1137.72    24.9 1125.43    48.8 1115.44    69.4 1105.50    80.7 1101.89
   130.5 1090.13   261.2 1039.72   270.4 1036.76   346.6 1014.48   398.4  998.08
   447.1  984.21   489.6  978.25   509.2  976.51   520.3  975.99   524.2  976.36
   592.8  982.81   615.5  984.05   660.9  988.19   688.7  989.62   708.7  993.88
   716.8  998.45   730.4 1003.53   744.6 1005.72   759.0 1009.38   778.4 1011.89
   814.1 1014.72   852.5 1013.55   879.5 1011.51   938.2 1010.89   950.3 1010.06
#Mann= 3 , 0 , 0
       0     0.1       0   509.2   0.045       0   524.2     0.1       0
Bank Sta=   509.2,   524.2
Exp/Cntr=0.3,0.1

Type RM Length L Ch R = 1 ,16429.1,411.9,400,394.244
XS GIS Cut Line= 3
     1750043.613      314887.063     1750135.110      315427.551
     1750277.884      315898.216
#Sta/Elev= 30
       0 1162.59    24.3 1152.76    38.3 1145.73    76.2 1129.07   102.2 1118.23
   119.0 1112.43   143.6 1102.98   156.8 1098.53   173.7 1092.01   189.8 1087.35
   251.3 1061.53   270.9 1054.73   336.0 1026.70   361.5 1011.49   397.6  987.44
   412.0  979.42   423.4  976.83   540.7  974.99   555.7  975.51   669.3  979.70
   728.0  983.96   752.9  984.15   788.1  983.65   816.3  987.06   827.3  989.11
   864.2  998.72   902.0 1002.68   929.9 1006.89   980.3 1014.91  1040.0 1025.53
#Mann= 3 , 0 , 0
       0     0.1       0   540.7   0.045       0   555.7     0.1       0
Bank Sta=   540.7,   555.7
Exp/Cntr=0.3,0.1

Type RM Length L Ch R = 1 ,16029.1,402.835,400,394.257
XS GIS Cut Line= 3
     1749486.086      315134.625     1749815.665      315536.020
     1750073.209      315961.252
#Sta/Elev= 30
       0 1087.43    25.3 1086.32    68.9 1082.72    89.5 1077.47   110.1 1073.43
   125.5 1064.19   134.4 1054.97   156.2 1035.50   171.6 1029.26   186.9 1028.71
   325.0 1032.95   341.1 1029.67   392.3 1008.72   417.0  996.71   446.8  983.12
   455.6  979.75   476.7  974.99   511.9  970.26   518.8  969.33   521.0  969.63
   526.9  971.69   544.8  977.53   552.1  978.10   574.7  978.90   795.2  982.89
   864.5  999.54   884.2 1001.29   907.8 1004.97  1004.2 1023.58  1016.5 1026.48
#Mann= 3 , 0 , 0
       0     0.1       0   511.9   0.045       0   526.9     0.1       0
Bank Sta=   511.9,   526.9
Exp/Cntr=0.3,0.1