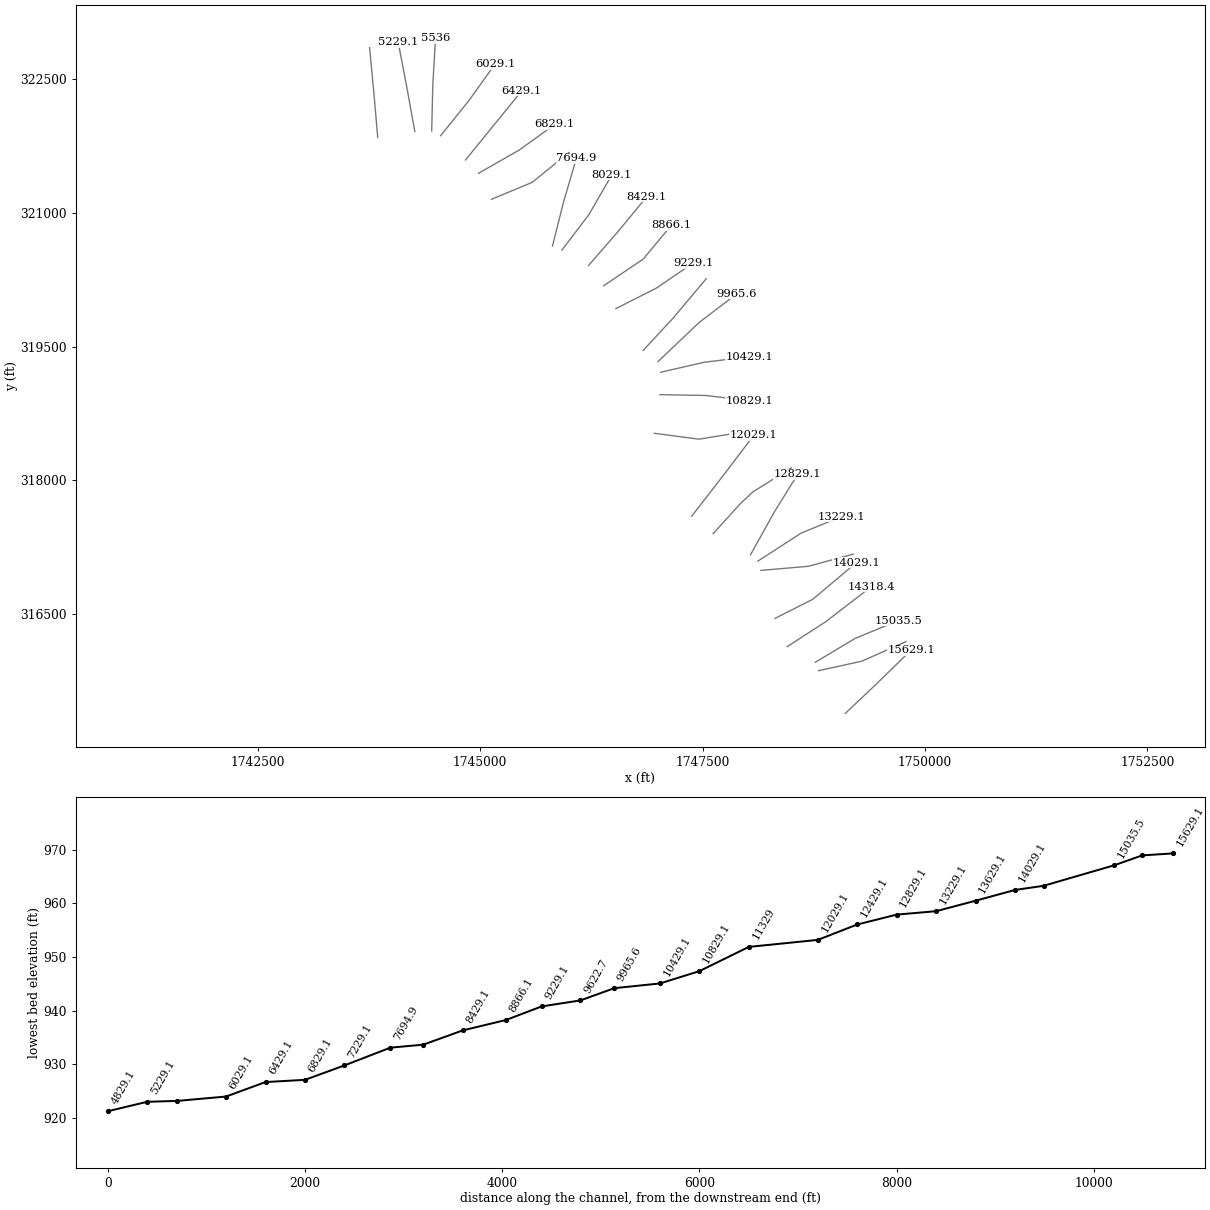
HEC-RAS study ShinsRn.prj: ShinsRn

--- ShinsRn.g01 (geometry) --- (continued)

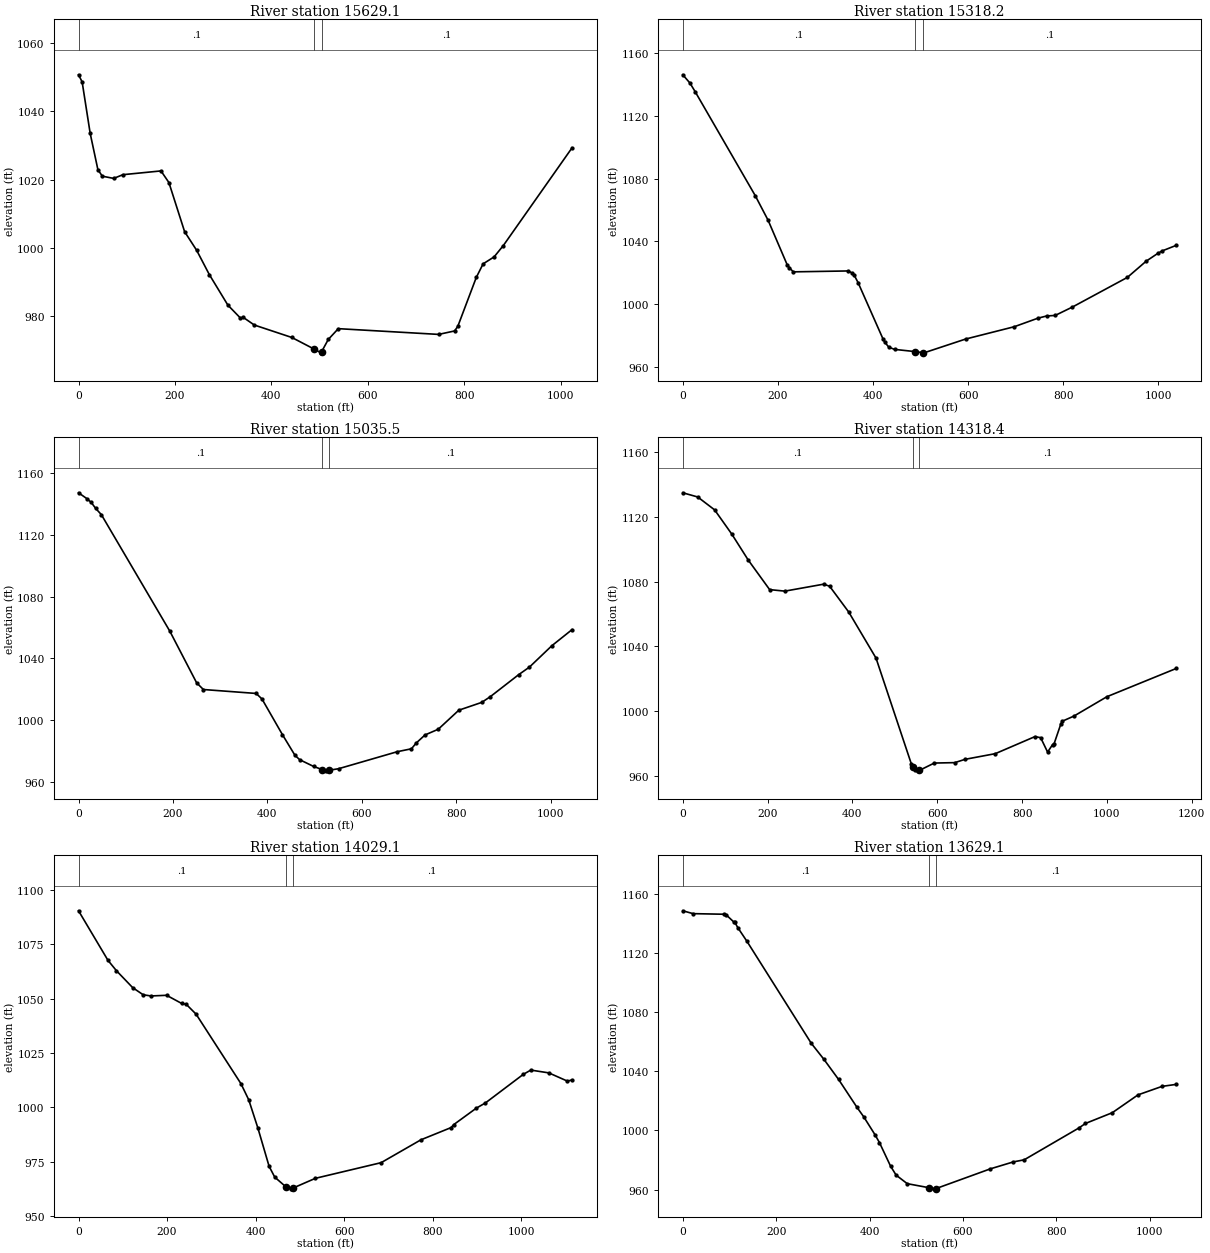
Type RM Length L Ch R = 1 ,15629.1,322.578,310.884,303.283
XS GIS Cut Line= 3
     1749104.685      315380.946     1749465.425      315722.363
     1749842.607      316090.338
#Sta/Elev= 30
       0 1050.62     7.5 1048.53    24.2 1033.46    40.2 1022.86    49.4 1020.97
    72.9 1020.32    92.1 1021.41   171.0 1022.51   187.4 1019.12   220.0 1004.75
   245.0  999.30   271.3  992.19   309.8  983.26   335.5  979.53   341.8  979.67
   364.6  977.45   442.4  973.81   489.2  970.38   502.9  969.32   504.2  969.66
   518.0  973.24   538.8  976.39   746.8  974.71   780.0  975.72   786.7  977.09
   825.0  991.38   839.1  995.34   861.9  997.37   881.0 1000.68  1023.6 1029.27
#Mann= 3 , 0 , 0
       0     0.1       0   489.2   0.045       0   504.2     0.1       0
Bank Sta=   489.2,   504.2
Exp/Cntr=0.3,0.1

Type RM Length L Ch R = 1 ,15318.2,276.702,282.735,281.816
XS GIS Cut Line= 3
     1748805.650      315860.737     1749288.079      315966.595
     1749785.503      316186.287
#Sta/Elev= 30
       0 1146.32    14.9 1141.10    25.9 1135.61   152.2 1069.30   179.4 1053.52
   219.5 1025.13   224.1 1023.25   232.4 1020.61   348.2 1021.19   355.4 1019.96
   360.4 1018.48   368.6 1013.73   421.2  977.66   425.2  975.55   433.3  972.53
   445.2  971.16   489.1  969.72   504.1  969.08   507.1  968.95   594.7  977.75
   697.0  985.61   746.7  991.05   765.0  992.46   783.0  992.81   819.4  998.19
   934.8 1017.08   974.3 1027.41   998.4 1032.32  1008.1 1033.99  1037.7 1037.53
#Mann= 3 , 0 , 0
       0     0.1       0   489.1   0.045       0   504.1     0.1       0
Bank Sta=   489.1,   504.1
Exp/Cntr=0.3,0.1

Type RM Length L Ch R = 1 ,15035.5,714.443,717.12,722.193
XS GIS Cut Line= 3
     1748766.192      315954.297     1749210.700      316220.398
     1749697.532      316422.844
#Sta/Elev= 30
       0 1147.41    17.3 1143.69    26.9 1141.15    36.4 1137.24    48.3 1133.25
   193.3 1057.68   250.1 1024.18   264.4 1019.84   376.2 1017.29   388.5 1013.69
   431.7  990.62   458.3  977.18   468.3  974.34   497.8  969.96   516.2  967.91
   523.7  967.11   531.2  967.53   550.6  968.48   675.1  979.53   705.0  981.41
   715.1  985.16   733.8  990.39   761.7  994.07   805.3 1006.43   853.8 1011.49
   872.1 1015.23   932.2 1029.51   954.9 1034.39  1002.2 1048.21  1045.1 1058.69
#Mann= 3 , 0 , 0
       0     0.1       0   516.2   0.045       0   531.2     0.1       0
Bank Sta=   516.2,   531.2
Exp/Cntr=0.3,0.1

Type RM Length L Ch R = 1 ,14318.4,293.459,289.261,290.359
XS GIS Cut Line= 3
     1748451.333      316130.220     1748882.971      316409.065
     1749398.260      316804.921
#Sta/Elev= 30
       0 1134.72    35.2 1132.13    75.1 1124.17   115.8 1109.14   154.2 1093.29
   204.8 1075.01   240.7 1074.08   332.0 1078.36   346.2 1077.11   391.3 1061.18
   455.6 1032.80   539.0  967.48   543.1  965.71   547.4  963.92   555.9  963.28
   558.1  963.58   593.0  968.08   641.3  968.34   665.6  970.38   736.9  973.87
   830.3  984.38   843.8  983.73   860.2  974.84   871.8  979.38   875.2  979.76
   891.8  992.45   895.3  993.93   922.5  997.07  1000.0 1008.98  1163.7 1026.42
#Mann= 3 , 0 , 0
       0     0.1       0   543.1   0.045       0   558.1     0.1       0
Bank Sta=   543.1,   558.1
Exp/Cntr=0.3,0.1

Type RM Length L Ch R = 1 ,14029.1,408.803,400,389.973
XS GIS Cut Line= 3
     1748315.192      316447.701     1748739.962      316662.606
     1749228.970      317074.105
#Sta/Elev= 30
       0 1090.35    66.5 1067.57    85.6 1062.81   122.3 1055.02   146.1 1051.73
   163.6 1051.19   199.0 1051.49   233.2 1047.73   243.2 1047.38   265.6 1042.83
   366.9 1010.89   384.6 1003.43   405.2  990.49   430.6  972.85   443.3  967.90
   468.5  963.43   480.1  962.51   483.5  962.77   535.2  967.35   683.7  974.54
   773.6  985.05   841.7  990.67   847.5  992.00   898.9  999.62   919.4 1002.01
  1004.8 1015.13  1021.9 1017.11  1062.6 1015.82  1104.5 1012.04  1115.1 1012.57
#Mann= 3 , 0 , 0
       0     0.1       0   468.5   0.045       0   483.5     0.1       0
Bank Sta=   468.5,   483.5
Exp/Cntr=0.3,0.1

Type RM Length L Ch R = 1 ,13629.1,388.187,400,403.201
XS GIS Cut Line= 3
     1748156.355      316986.397     1748689.153      317032.493
     1749193.180      317168.826
#Sta/Elev= 30
       0 1148.68    22.1 1146.74    87.9 1146.34    93.5 1145.75   108.8 1141.24
   111.3 1140.92   117.8 1137.28   137.5 1127.96   275.2 1058.97   301.9 1048.28
   333.7 1034.51   373.2 1015.58   387.8 1009.10   411.5  997.18   421.1  991.85
   444.9  975.90   456.9  969.76   480.7  964.00   527.3  961.26   540.4  960.50
   542.3  960.68   658.8  974.04   708.1  978.75   731.1  980.14   847.9 1001.62
   862.3 1004.74   919.9 1012.04   974.9 1024.10  1026.4 1029.85  1056.9 1031.20
#Mann= 3 , 0 , 0
       0     0.1       0   527.3   0.045       0   542.3     0.1       0
Bank Sta=   527.3,   542.3
Exp/Cntr=0.3,0.1

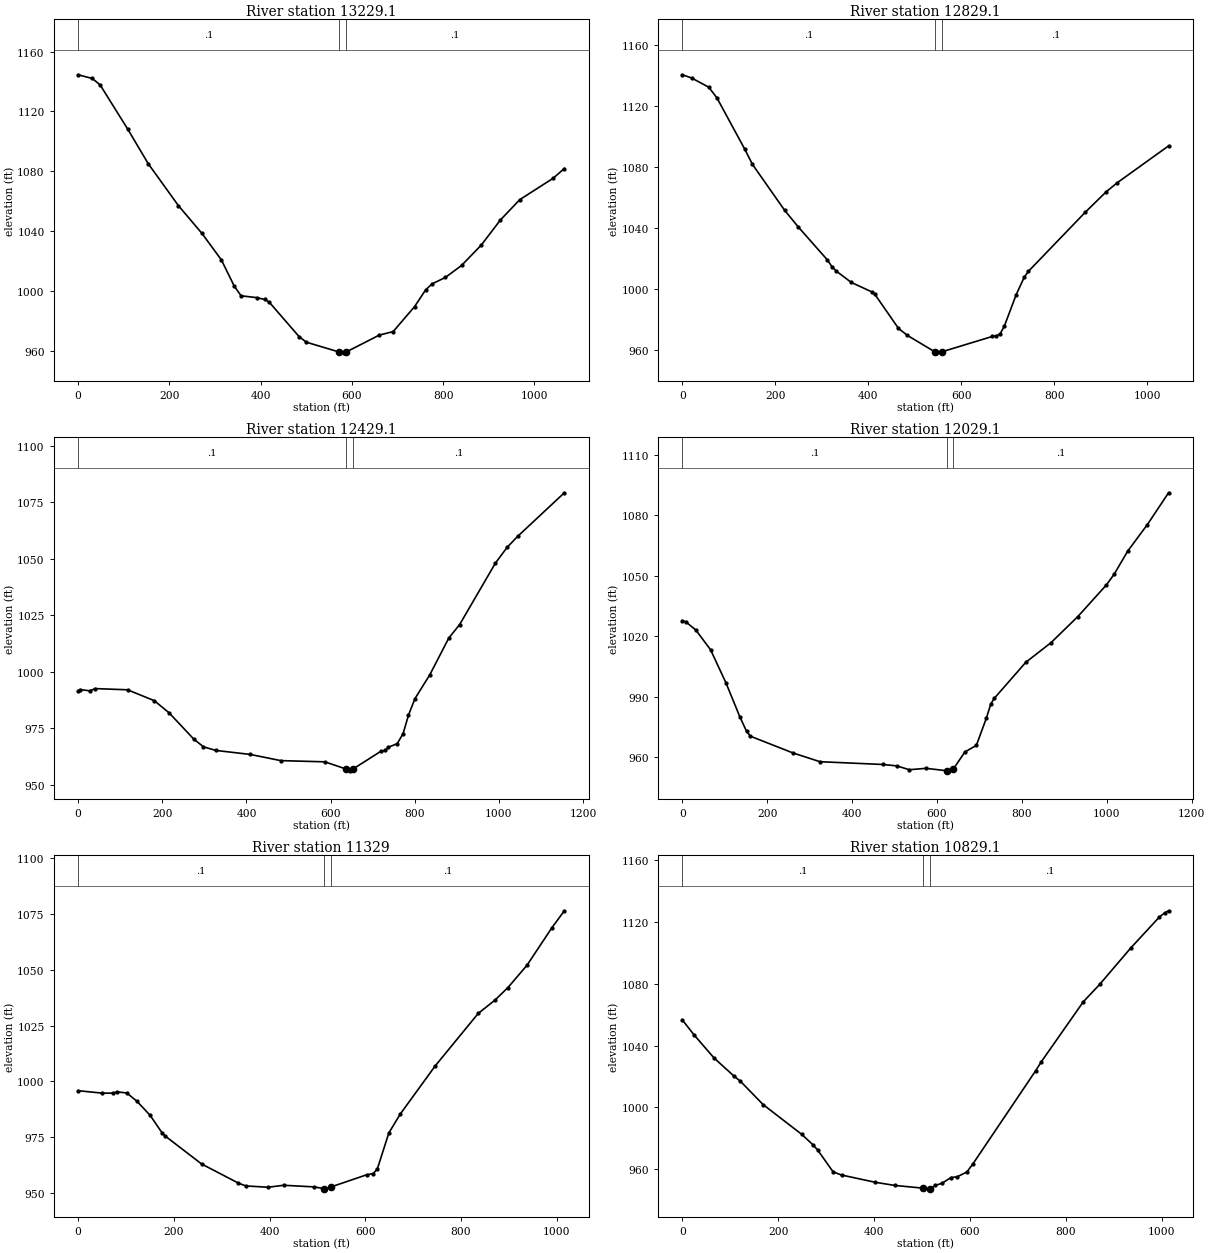
Type RM Length L Ch R = 1 ,13229.1,388.79,400,414.299
XS GIS Cut Line= 3
     1748122.458      317090.905     1748608.662      317405.403
     1749058.925      317590.009
#Sta/Elev= 30
       0 1144.53    30.9 1142.06    48.0 1137.81   109.0 1108.01   153.4 1085.15
   219.7 1057.03   271.2 1038.49   313.8 1020.79   342.1 1003.21   357.1  996.69
   391.4  995.49   408.6  994.25   418.6  992.53   484.3  969.40   500.1  965.67
   571.6  959.15   582.1  958.55   586.6  958.97   660.0  970.41   690.5  972.77
   737.4  989.45   761.8 1000.70   775.7 1004.65   805.1 1009.01   840.3 1016.97
   883.7 1030.64   925.6 1047.43   968.2 1061.05  1041.1 1075.30  1065.7 1081.84
#Mann= 3 , 0 , 0
       0     0.1       0   571.6   0.045       0   586.6     0.1       0
Bank Sta=   571.6,   586.6
Exp/Cntr=0.3,0.1

Type RM Length L Ch R = 1 ,12829.1,405.297,400,390.181
XS GIS Cut Line= 3
     1748039.737      317162.655     1748308.189      317644.725
     1748569.040      318064.208
#Sta/Elev= 30
       0 1140.40    19.8 1138.31    56.8 1132.23    74.3 1125.23   134.5 1091.39
   150.8 1081.55   219.9 1051.47   249.2 1040.55   311.7 1018.95   322.3 1014.20
   331.4 1011.47   363.1 1004.16   407.3  997.93   413.9  996.36   464.8  973.96
   483.6  969.42   544.3  958.33   546.1  957.91   559.3  958.69   666.6  968.66
   675.0  968.92   683.7  970.55   692.3  975.27   718.1  996.18   735.4 1007.60
   744.0 1011.32   866.9 1050.28   910.9 1063.40   935.1 1069.50  1045.7 1093.72
#Mann= 3 , 0 , 0
       0     0.1       0   544.3   0.045       0   559.3     0.1       0
Bank Sta=   544.3,   559.3
Exp/Cntr=0.3,0.1

Type RM Length L Ch R = 1 ,12429.1,398.036,400,407.824
XS GIS Cut Line= 4
     1747619.789      317399.653     1747929.305      317740.120
     1748064.266      317866.471     1748496.881      318137.685
#Sta/Elev= 30
       0  991.31     4.7  992.07    27.0  991.51    40.9  992.49   117.3  991.96
   181.1  987.13   216.3  981.74   274.6  970.16   297.9  966.70   327.2  965.11
   409.3  963.33   481.7  960.59   586.3  960.06   637.5  956.83   646.2  956.07
   652.5  956.78   719.5  964.73   730.4  965.10   737.1  966.49   758.4  968.12
   772.4  972.55   785.1  980.73   800.4  987.99   835.9  998.63   880.9 1014.86
   906.8 1020.86   991.8 1048.06  1019.5 1055.02  1044.4 1059.86  1155.6 1079.21
#Mann= 3 , 0 , 0
       0     0.1       0   637.5   0.045       0   652.5     0.1       0
Bank Sta=   637.5,   652.5
Exp/Cntr=0.3,0.1

Type RM Length L Ch R = 1 ,12029.1,717.678,700.126,682.039
XS GIS Cut Line= 3
     1747378.367      317594.648     1747764.768      318093.603
     1748075.780      318503.200
#Sta/Elev= 30
       0 1027.74     8.2 1027.11    31.4 1023.15    66.3 1013.32   102.5  996.94
   135.5  979.94   151.2  972.81   160.4  970.37   260.4  962.09   324.2  957.73
   473.1  956.35   505.1  955.66   534.6  953.75   574.1  954.44   623.6  953.23
   624.8  953.20   638.6  954.20   665.6  962.57   692.6  965.83   715.9  979.19
   726.5  986.29   734.6  989.12   809.1 1007.07   868.7 1016.84   931.8 1029.79
   999.0 1045.46  1017.8 1050.94  1048.8 1062.13  1095.6 1075.44  1145.4 1091.19
#Mann= 3 , 0 , 0
       0     0.1       0   623.6   0.045       0   638.6     0.1       0
Bank Sta=   623.6,   638.6
Exp/Cntr=0.3,0.1

Type RM Length L Ch R = 1 ,11329,501.978,499.875,493.322
XS GIS Cut Line= 3
     1746959.258      318525.656     1747460.359      318459.865
     1747964.365      318542.068
#Sta/Elev= 30
       0  995.83    49.9  994.75    73.8  994.75    80.6  995.33   101.7  994.81
   122.9  991.10   150.4  984.80   175.3  976.99   181.6  975.59   258.0  963.02
   334.6  954.49   350.2  953.20   397.1  952.60   429.5  953.49   492.6  952.77
   513.8  952.01   516.9  951.89   528.8  952.77   602.7  958.16   616.7  958.74
   625.2  960.76   649.3  976.90   673.3  985.41   746.2 1006.92   836.1 1030.43
   870.8 1036.32   898.2 1042.00   938.0 1051.98   989.8 1068.70  1016.1 1076.39
#Mann= 3 , 0 , 0
       0     0.1       0   513.8   0.045       0   528.8     0.1       0
Bank Sta=   513.8,   528.8
Exp/Cntr=0.3,0.1

Type RM Length L Ch R = 1 ,10829.1,394.325,400,405.591
XS GIS Cut Line= 3
     1747020.980      318959.676     1747530.302      318950.749
     1748032.209      318893.772
#Sta/Elev= 30
       0 1056.61    24.1 1047.06    66.5 1031.88   108.3 1020.15   120.8 1017.07
   168.7 1001.82   249.0  982.64   272.7  975.80   282.5  972.41   314.6  958.34
   332.1  956.32   402.9  951.59   443.1  949.59   501.9  947.83   516.9  947.40
   517.5  947.38   527.7  949.57   542.5  951.10   560.3  954.68   573.4  955.18
   593.8  958.31   606.6  963.68   737.2 1023.78   749.1 1029.63   836.5 1068.33
   870.8 1079.63   935.3 1103.06   995.6 1123.29  1006.2 1125.83  1014.5 1127.24
#Mann= 3 , 0 , 0
       0     0.1       0   501.9   0.045       0   516.9     0.1       0
Bank Sta=   501.9,   516.9
Exp/Cntr=0.3,0.1

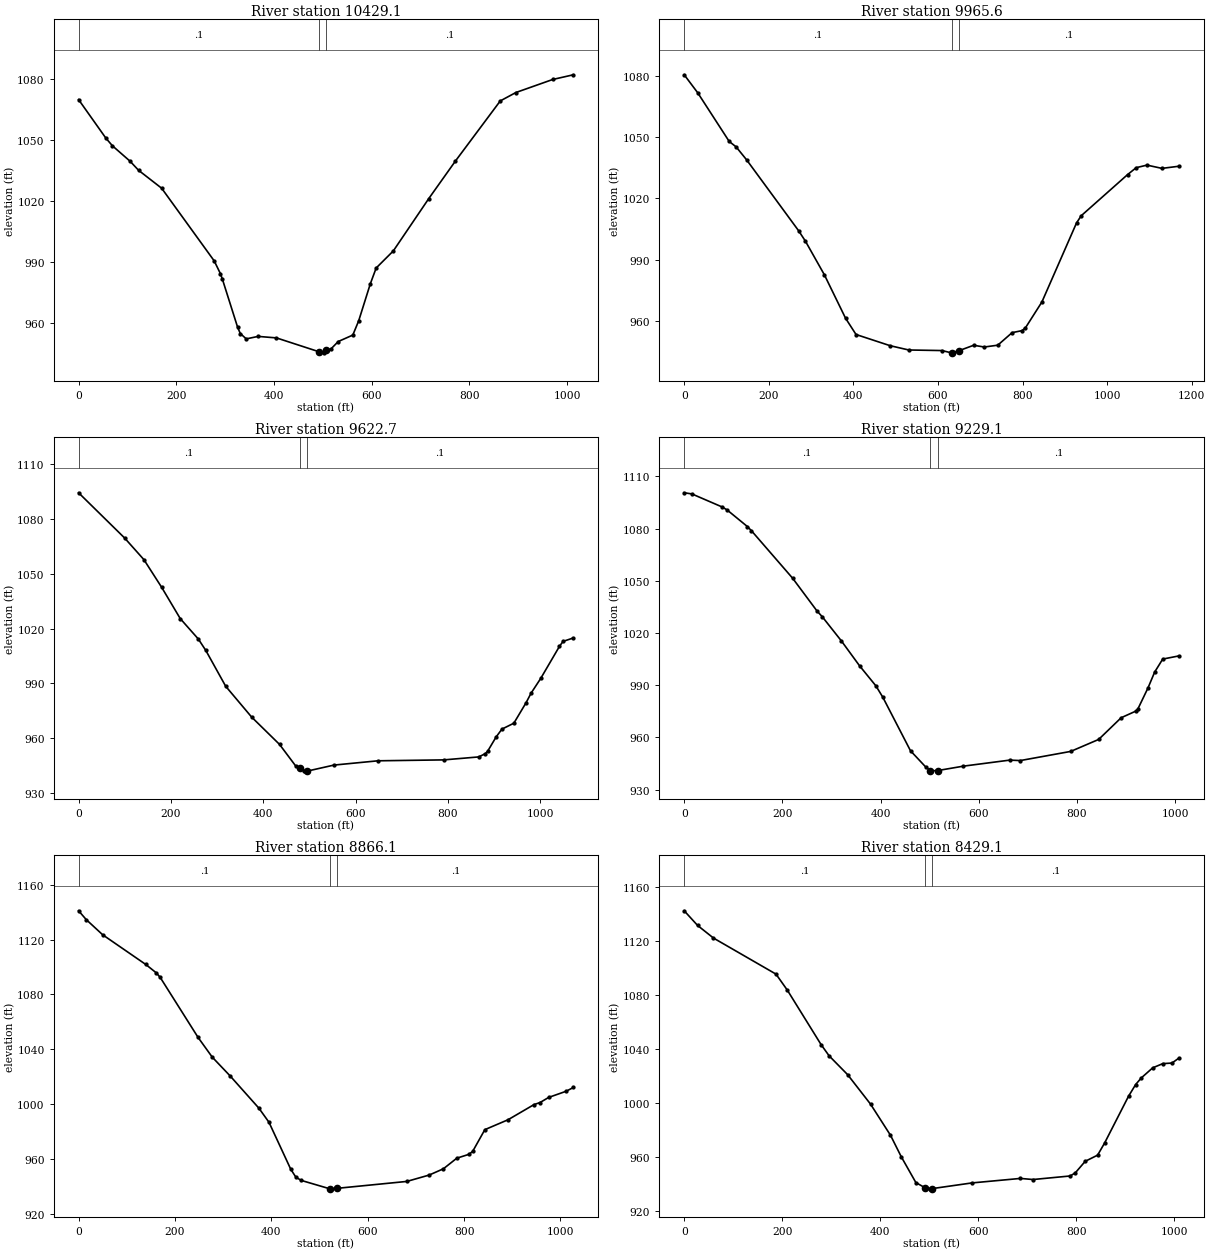
Type RM Length L Ch R = 1 ,10429.1,451.924,463.539,475.571
XS GIS Cut Line= 3
     1747030.434      319211.503     1747517.643      319323.535
     1748026.773      319384.330
#Sta/Elev= 30
       0 1069.72    56.0 1050.70    69.4 1046.95   105.2 1039.43   123.0 1034.88
   170.0 1026.10   277.6  990.32   290.2  984.10   294.4  981.29   325.5  957.67
   331.0  954.59   343.2  951.95   367.5  953.17   405.0  952.43   492.4  945.59
   501.5  945.08   507.4  946.26   516.7  947.04   531.5  950.65   561.3  953.83
   573.3  960.84   597.2  979.12   609.1  986.84   644.2  995.25   716.7 1020.99
   771.1 1039.41   863.1 1069.07   895.1 1073.21   970.4 1079.62  1012.7 1081.94
#Mann= 3 , 0 , 0
       0     0.1       0   492.4   0.045       0   507.4     0.1       0
Bank Sta=   492.4,   507.4
Exp/Cntr=0.3,0.1

Type RM Length L Ch R = 1 ,9965.6,340.924,342.874,347.889
XS GIS Cut Line= 3
     1747000.107      319330.987     1747461.936      319770.544
     1747885.972      320092.440
#Sta/Elev= 30
       0 1080.68    31.8 1071.89   106.4 1047.96   122.8 1045.28   147.5 1038.95
   270.7 1004.08   286.7  998.99   331.4  982.52   381.6  961.16   406.3  953.20
   487.2  947.69   531.0  945.60   609.6  945.32   631.6  944.20   634.1  944.35
   649.1  945.21   684.4  947.91   709.5  947.06   741.4  947.95   775.4  954.12
   798.9  955.10   806.9  956.48   845.8  969.16   927.7 1007.97   938.6 1011.46
  1048.2 1031.65  1068.8 1035.09  1094.3 1036.34  1129.6 1034.74  1169.9 1035.79
#Mann= 3 , 0 , 0
       0     0.1       0   634.1   0.045       0   649.1     0.1       0
Bank Sta=   634.1,   649.1
Exp/Cntr=0.3,0.1

Type RM Length L Ch R = 1 ,9622.7,401.622,393.586,387.48
XS GIS Cut Line= 3
     1746833.194      319456.522     1747163.152      319812.419
     1747541.295      320260.767
#Sta/Elev= 30
       0 1094.48    99.5 1069.72   141.5 1057.79   180.1 1042.55   220.2 1025.45
   259.3 1014.27   275.6 1007.97   318.7  988.31   374.8  971.43   435.3  956.42
   470.6  944.49   479.2  943.38   488.0  942.04   494.2  941.96   497.8  941.92
   553.2  945.08   648.7  947.43   791.1  947.93   867.0  949.56   881.3  951.40
   886.3  952.75   904.5  960.52   917.1  964.82   942.9  968.06   969.5  979.35
   980.2  984.53  1001.1  992.63  1041.7 1010.22  1049.4 1012.93  1071.8 1014.83
#Mann= 3 , 0 , 0
       0     0.1       0   479.2   0.045       0   494.2     0.1       0
Bank Sta=   479.2,   494.2
Exp/Cntr=0.3,0.1

Type RM Length L Ch R = 1 ,9229.1,360.109,362.979,367.719
XS GIS Cut Line= 3
     1746526.640      319926.145     1746980.767      320155.718
     1747393.273      320436.547
#Sta/Elev= 30
       0 1100.54    15.6 1099.89    77.4 1092.37    87.4 1090.68   128.9 1081.09
   137.0 1078.73   220.9 1051.44   270.6 1032.60   281.3 1029.31   320.3 1015.40
   357.2 1001.15   390.5  989.62   404.6  983.09   461.0  952.32   492.0  943.01
   501.4  940.95   502.1  940.80   516.4  940.96   568.9  943.50   663.1  946.96
   684.6  946.70   787.4  951.96   844.3  958.84   890.1  971.30   921.2  975.26
   924.2  976.35   944.8  988.43   958.4  997.55   974.8 1005.00  1007.9 1006.83
#Mann= 3 , 0 , 0
       0     0.1       0   501.4   0.045       0   516.4     0.1       0
Bank Sta=   501.4,   516.4
Exp/Cntr=0.3,0.1

Type RM Length L Ch R = 1 ,8866.1,430.886,437.021,438.919
XS GIS Cut Line= 3
     1746389.955      320182.785     1746833.619      320482.430
     1747147.964      320860.003
#Sta/Elev= 30
       0 1140.96    16.0 1134.48    50.0 1123.46   139.4 1101.83   161.1 1095.75
   169.2 1092.47   248.0 1048.61   277.4 1034.25   314.8 1020.44   374.1  997.08
   395.0  986.84   440.2  952.60   450.9  946.75   462.0  944.41   521.6  938.26
   521.9  938.27   536.9  938.65   681.1  943.66   727.5  948.31   757.0  952.87
   784.8  960.60   809.4  963.35   817.7  965.51   843.0  981.40   891.1  988.61
   945.0  999.67   957.5 1001.17   975.6 1004.92  1011.6 1009.38  1026.7 1012.15
#Mann= 3 , 0 , 0
       0     0.1       0   521.9   0.045       0   536.9     0.1       0
Bank Sta=   521.9,   536.9
Exp/Cntr=0.3,0.1

Type RM Length L Ch R = 1 ,8429.1,397.933,400,405.24
XS GIS Cut Line= 3
     1746220.035      320410.872     1746547.256      320787.286
     1746872.827      321181.399
#Sta/Elev= 30
       0 1142.54    27.4 1131.64    59.7 1122.32   187.4 1095.56   210.4 1083.75
   279.3 1043.37   295.8 1034.97   333.5 1021.05   380.3  999.19   421.1  976.07
   443.2  960.05   472.9  940.98   491.3  937.20   501.8  936.33   506.3  936.51
   587.5  940.72   686.3  944.05   712.1  943.24   787.9  945.87   798.4  948.20
   818.6  956.75   843.9  961.31   858.3  970.38   907.0 1004.98   921.6 1013.70
   933.0 1018.56   956.4 1026.08   977.1 1029.20   995.7 1029.60  1010.0 1033.33
#Mann= 3 , 0 , 0
       0     0.1       0   491.3   0.045       0   506.3     0.1       0
Bank Sta=   491.3,   506.3
Exp/Cntr=0.3,0.1

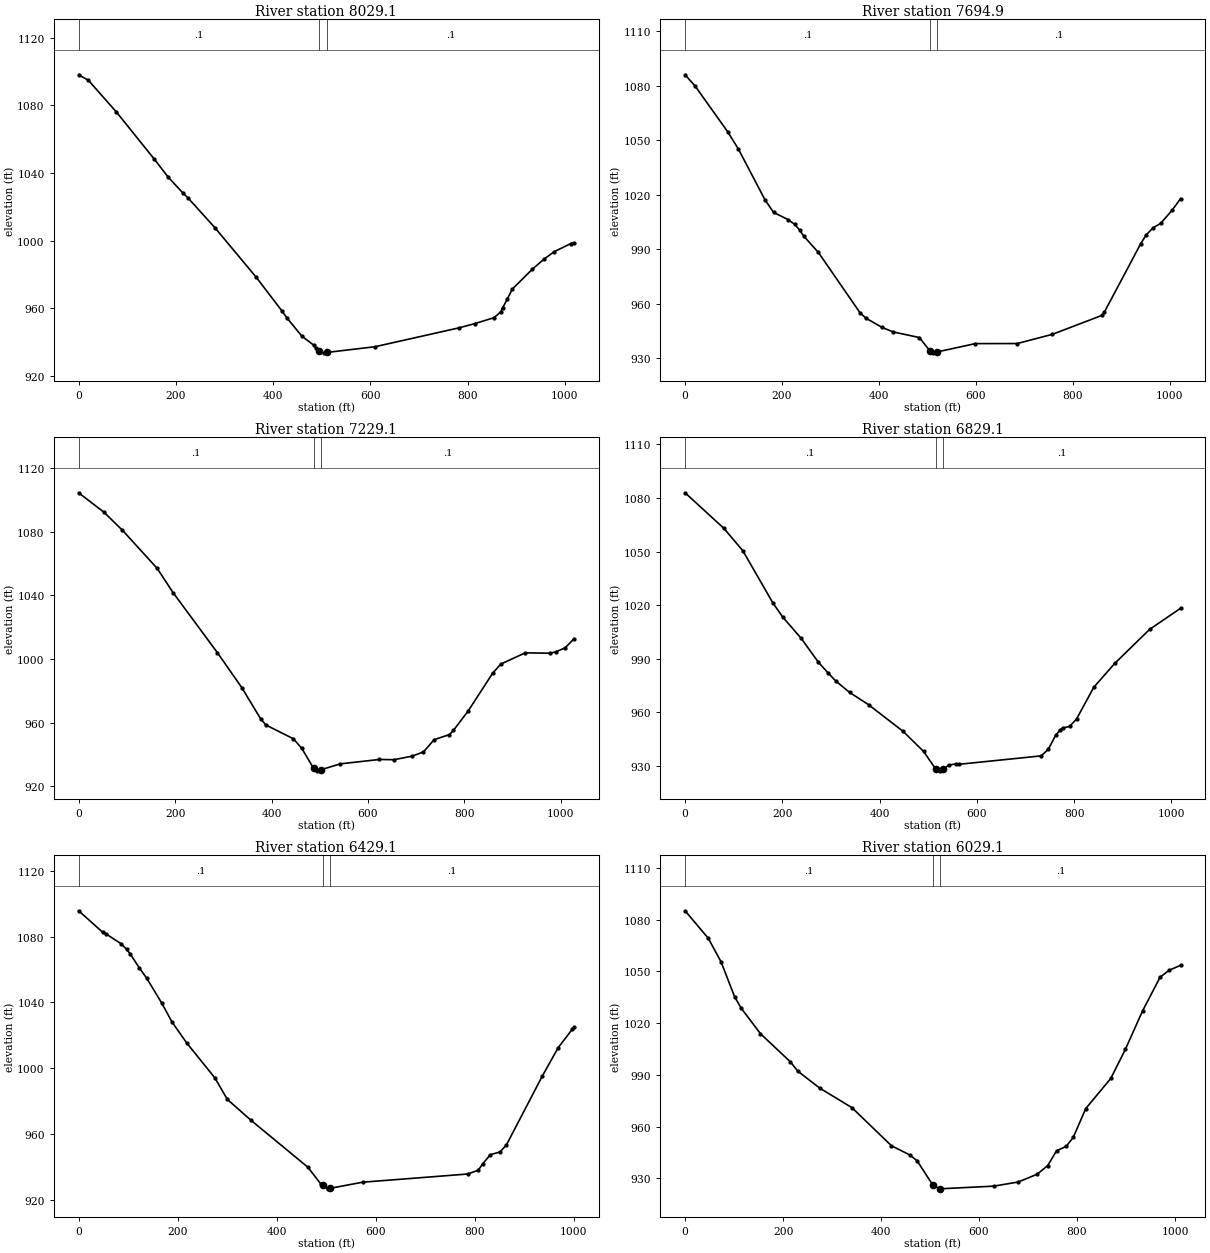
Type RM Length L Ch R = 1 ,8029.1,325.805,334.262,337.858
XS GIS Cut Line= 3
     1745919.437      320582.076     1746223.685      320982.016
     1746481.815      321429.337
#Sta/Elev= 30
       0 1098.09    20.1 1094.82    77.8 1076.03   155.6 1048.20   184.2 1037.56
   214.0 1028.32   224.7 1025.34   280.4 1007.62   365.3  978.33   417.5  958.67
   428.3  954.31   458.9  943.60   483.7  938.14   488.7  936.28     495  934.59
   503.7  933.67     510  933.89   609.5  937.29   782.0  948.43   814.2  950.91
   854.3  954.47   868.0  957.87   871.9  960.31   881.7  965.52   891.7  971.33
   932.9  983.11   957.0  989.08   977.6  993.42  1012.0  998.29  1019.0  998.76
#Mann= 3 , 0 , 0
       0     0.1       0     495   0.045       0     510     0.1       0
Bank Sta=     495,     510
Exp/Cntr=0.3,0.1

Type RM Length L Ch R = 1 ,7694.9,486.755,465.739,452.48
XS GIS Cut Line= 3
     1745813.510      320628.063     1745939.118      321126.223
     1746083.094      321614.134
#Sta/Elev= 30
       0 1085.93    20.9 1079.66    88.0 1054.56   110.1 1045.05   165.0 1017.12
   182.7 1010.26   212.3 1006.37   226.2 1003.69   236.1 1000.67   245.0  997.21
   275.1  988.26   360.9  955.15   373.0  952.20   406.1  947.12   428.9  944.62
   483.3  941.53   504.7  934.35   511.3  933.11   519.7  933.58   598.8  938.18
   685.2  938.22   757.5  943.25   860.0  953.68   865.0  955.44   940.3  993.17
   951.3  997.86   965.7 1001.86   981.3 1004.26  1004.5 1011.34  1022.5 1017.91
#Mann= 3 , 0 , 0
       0     0.1       0   504.7   0.045       0   519.7     0.1       0
Bank Sta=   504.7,   519.7
Exp/Cntr=0.3,0.1

Type RM Length L Ch R = 1 ,7229.1,397.172,400,398.552
XS GIS Cut Line= 3
     1745128.716      321153.324     1745585.572      321343.354
     1745999.495      321678.808
#Sta/Elev= 30
       0 1104.33    52.1 1092.24    90.8 1080.83   162.9 1056.87   195.9 1041.63
   287.9 1003.91   338.8  981.84   377.2  962.58   388.1  958.62   445.2  949.95
   462.6  943.99   487.3  931.34   495.2  929.80   502.3  930.46   542.7  934.19
   623.7  936.93   654.1  936.79   691.4  939.02   715.0  941.65   737.3  949.39
   768.9  952.53   777.3  955.22   807.9  967.42   858.3  990.96   875.4  996.80
   926.1 1003.86   976.7 1003.63   989.4 1004.42  1009.1 1007.09  1027.6 1012.80
#Mann= 3 , 0 , 0
       0     0.1       0   487.3   0.045       0   502.3     0.1       0
Bank Sta=   487.3,   502.3
Exp/Cntr=0.3,0.1

Type RM Length L Ch R = 1 ,6829.1,391.646,400,405.992
XS GIS Cut Line= 3
     1744983.393      321445.744     1745437.114      321704.616
     1745840.681      321993.808
#Sta/Elev= 30
       0 1082.93    80.0 1062.93   118.7 1050.46   180.7 1021.11   201.1 1013.17
   238.7 1001.36   274.2  987.92   293.6  982.08   309.5  977.52   338.3  971.04
   377.1  964.20   448.5  949.18   490.3  938.00   514.9  928.26   524.7  927.11
   529.9  927.93   541.7  930.19   557.0  931.10   563.1  930.77   732.3  935.50
   746.9  939.24   761.7  946.93   770.6  949.81   776.1  951.06   790.7  952.04
   804.9  956.16   840.3  973.95   883.4  987.32   955.2 1006.40  1018.9 1018.22
#Mann= 3 , 0 , 0
       0     0.1       0   514.9   0.045       0   529.9     0.1       0
Bank Sta=   514.9,   529.9
Exp/Cntr=0.3,0.1

Type RM Length L Ch R = 1 ,6429.1,399.945,400,401.326
XS GIS Cut Line= 3
     1744837.174      321595.612     1745153.164      321983.749
     1745469.154      322371.887
#Sta/Elev= 30
       0 1095.69    48.8 1082.59    54.6 1081.78    86.1 1075.60    97.2 1072.16
   103.6 1069.71   122.9 1060.85   137.5 1054.70   168.1 1039.49   188.4 1028.20
   218.1 1015.46   275.2  994.13   300.4  981.07   348.2  968.35   463.1  939.85
   488.9  929.76     493  928.90   502.9  926.70     508  927.01   573.5  930.73
   785.7  935.70   807.1  938.01   816.9  942.08   831.6  947.46   851.3  949.12
   864.2  953.42   936.8  995.33   968.7 1012.50   997.3 1023.73  1001.0 1024.89
#Mann= 3 , 0 , 0
       0     0.1       0     493   0.045       0     508     0.1       0
Bank Sta=     493,     508
Exp/Cntr=0.3,0.1

Type RM Length L Ch R = 1 ,6029.1,478.467,493.175,506.122
XS GIS Cut Line= 3
     1744556.997      321867.351     1744879.039      322267.493
     1745169.119      322672.299
#Sta/Elev= 30
       0 1085.20    47.2 1069.29    73.3 1055.65   101.1 1035.33   114.8 1028.61
   153.8 1013.96   214.7  997.69   230.1  992.23   274.8  982.40   340.6  971.07
   421.3  948.97   458.6  943.68   473.6  940.28   506.1  926.01   519.8  924.00
   521.1  924.03   630.1  925.56   680.0  927.96   718.8  932.48   740.3  937.52
   758.4  946.11   777.9  948.58   792.4  953.85   817.9  970.53   869.0  988.01
   898.7 1004.81   934.0 1027.22   969.7 1046.71   988.1 1050.70  1011.6 1053.63
#Mann= 3 , 0 , 0
       0     0.1       0   506.1   0.045       0   521.1     0.1       0
Bank Sta=   506.1,   521.1
Exp/Cntr=0.3,0.1

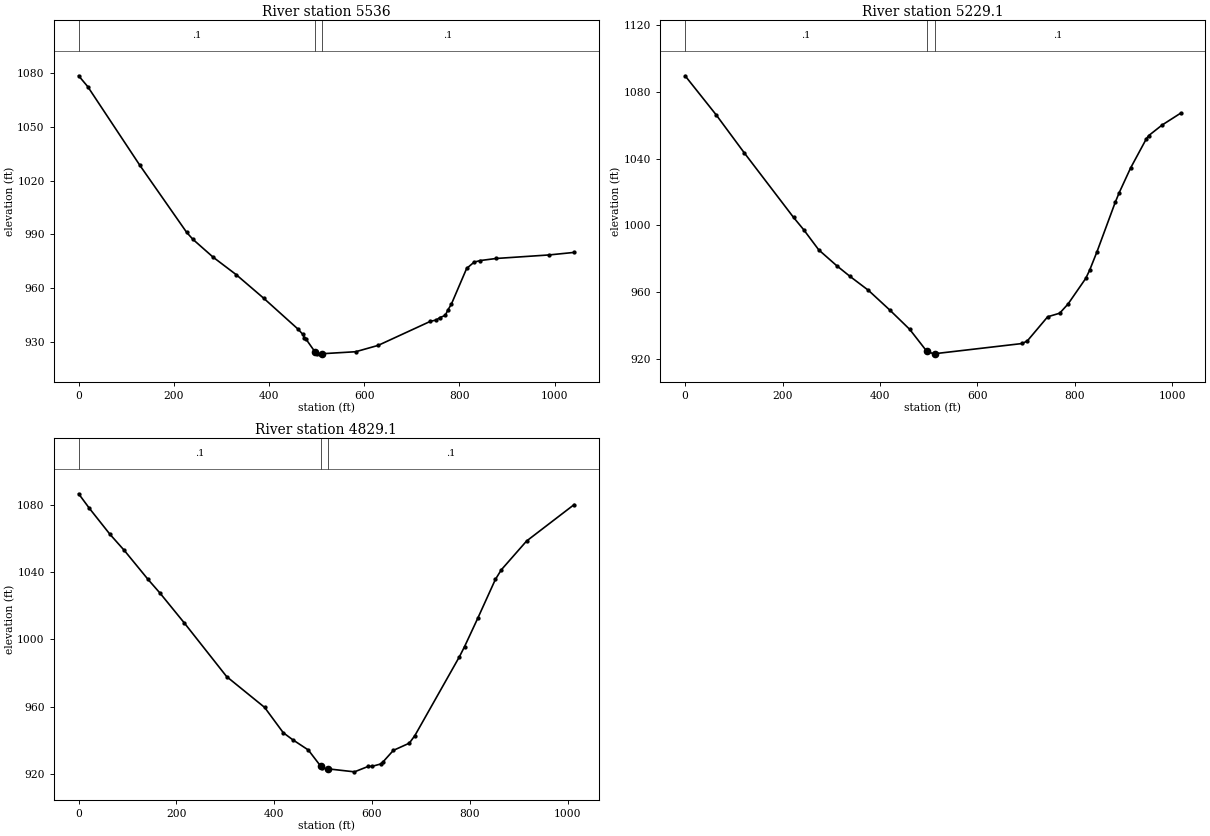
Type RM Length L Ch R = 1 ,5536,301.99,306.825,312.408
XS GIS Cut Line= 3
     1744456.709      321920.498     1744468.918      322435.474
     1744499.526      322960.668
#Sta/Elev= 30
       0 1078.59    19.0 1072.58   128.8 1028.48   227.0  991.07   240.2  987.16
   282.7  977.19   330.8  967.50   388.8  954.28   461.3  936.93   470.5  934.23
   474.4  932.28   478.3  931.21   496.4  924.37   500.3  923.29   506.1  923.19
   511.4  923.25   582.1  924.37   629.3  927.91   739.3  941.38   751.3  942.09
   759.1  943.49   770.4  944.66   775.4  947.50   783.2  950.98   815.3  970.93
   830.9  974.42   843.6  975.32   877.6  976.49   988.9  978.47  1041.2  979.88
#Mann= 3 , 0 , 0
       0     0.1       0   496.4   0.045       0   511.4     0.1       0
Bank Sta=   496.4,   511.4
Exp/Cntr=0.3,0.1

Type RM Length L Ch R = 1 ,5229.1,402.21,400,397.709
XS GIS Cut Line= 3
     1744266.885      321914.819     1744177.006      322411.273
     1744080.374      322914.597
#Sta/Elev= 30
       0 1089.68    63.6 1066.33   121.8 1043.35   222.7 1004.74   243.3  997.45
   274.4  985.30   311.2  975.84   338.7  969.38   376.2  961.10   420.5  949.16
   461.0  937.68   495.8  924.63     497  924.51   509.9  923.02     512  923.09
   692.3  929.22   702.7  930.89   744.1  945.23   768.7  947.37   785.8  952.84
   822.2  968.22   830.2  973.11   845.4  984.27   882.7 1013.79   890.9 1019.60
   914.1 1034.30   946.7 1051.95   951.5 1053.84   979.0 1060.17  1017.0 1067.26
#Mann= 3 , 0 , 0
       0     0.1       0     497   0.045       0     512     0.1       0
Bank Sta=     497,     512
Exp/Cntr=0.3,0.1

Type RM Length L Ch R = 1 ,4829.1,277.289,283.879,292.177
XS GIS Cut Line= 3
     1743850.290      321846.966     1743806.719      322347.828
     1743758.488      322856.239
#Sta/Elev= 30
       0 1086.51    22.0 1077.86    64.2 1062.38    93.2 1052.92   142.1 1035.57
   166.0 1027.62   216.1 1009.75   302.7  977.86   380.3  959.57   418.5  944.50
   437.4  940.43   469.8  934.22   495.3  924.52   498.2  923.41   510.3  923.03
   564.1  921.26   592.5  924.52   600.0  924.52   617.5  925.91   621.8  926.94
   643.6  934.01   676.2  938.29   687.7  942.84   778.8  989.71   789.2  995.67
   816.5 1012.70   852.2 1035.57   864.5 1041.36   916.1 1058.44  1013.4 1080.09
#Mann= 3 , 0 , 0
       0     0.1       0   495.3   0.045       0   510.3     0.1       0
Bank Sta=   495.3,   510.3
Exp/Cntr=0.3,0.1