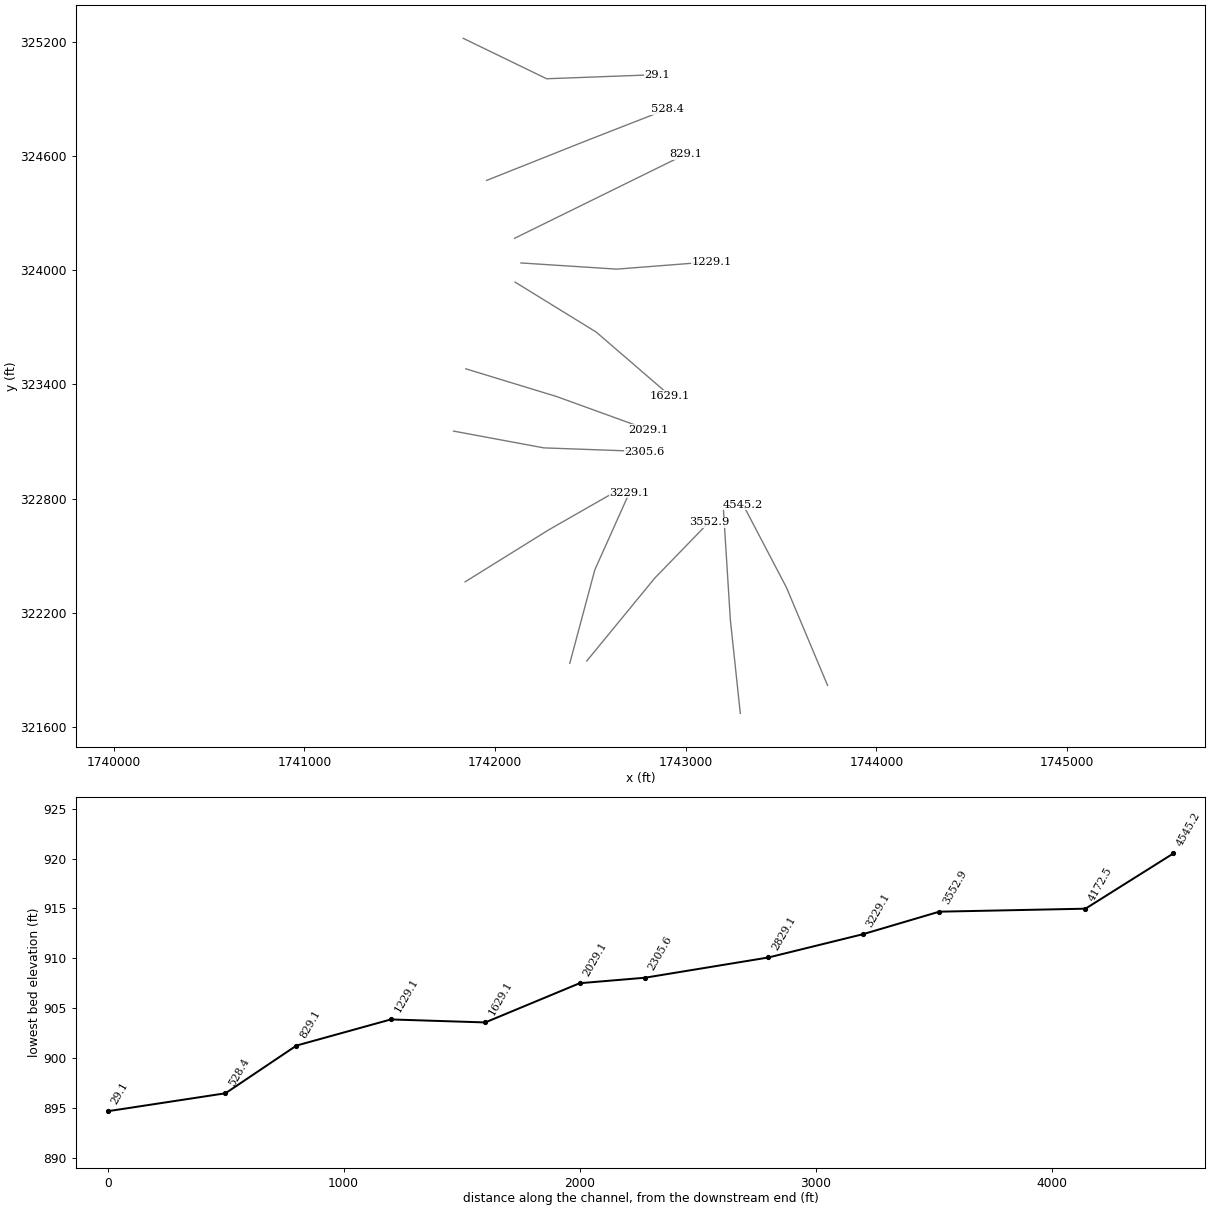
HEC-RAS study ShinsRn.prj: ShinsRn

--- ShinsRn.g01 (geometry) --- (continued)

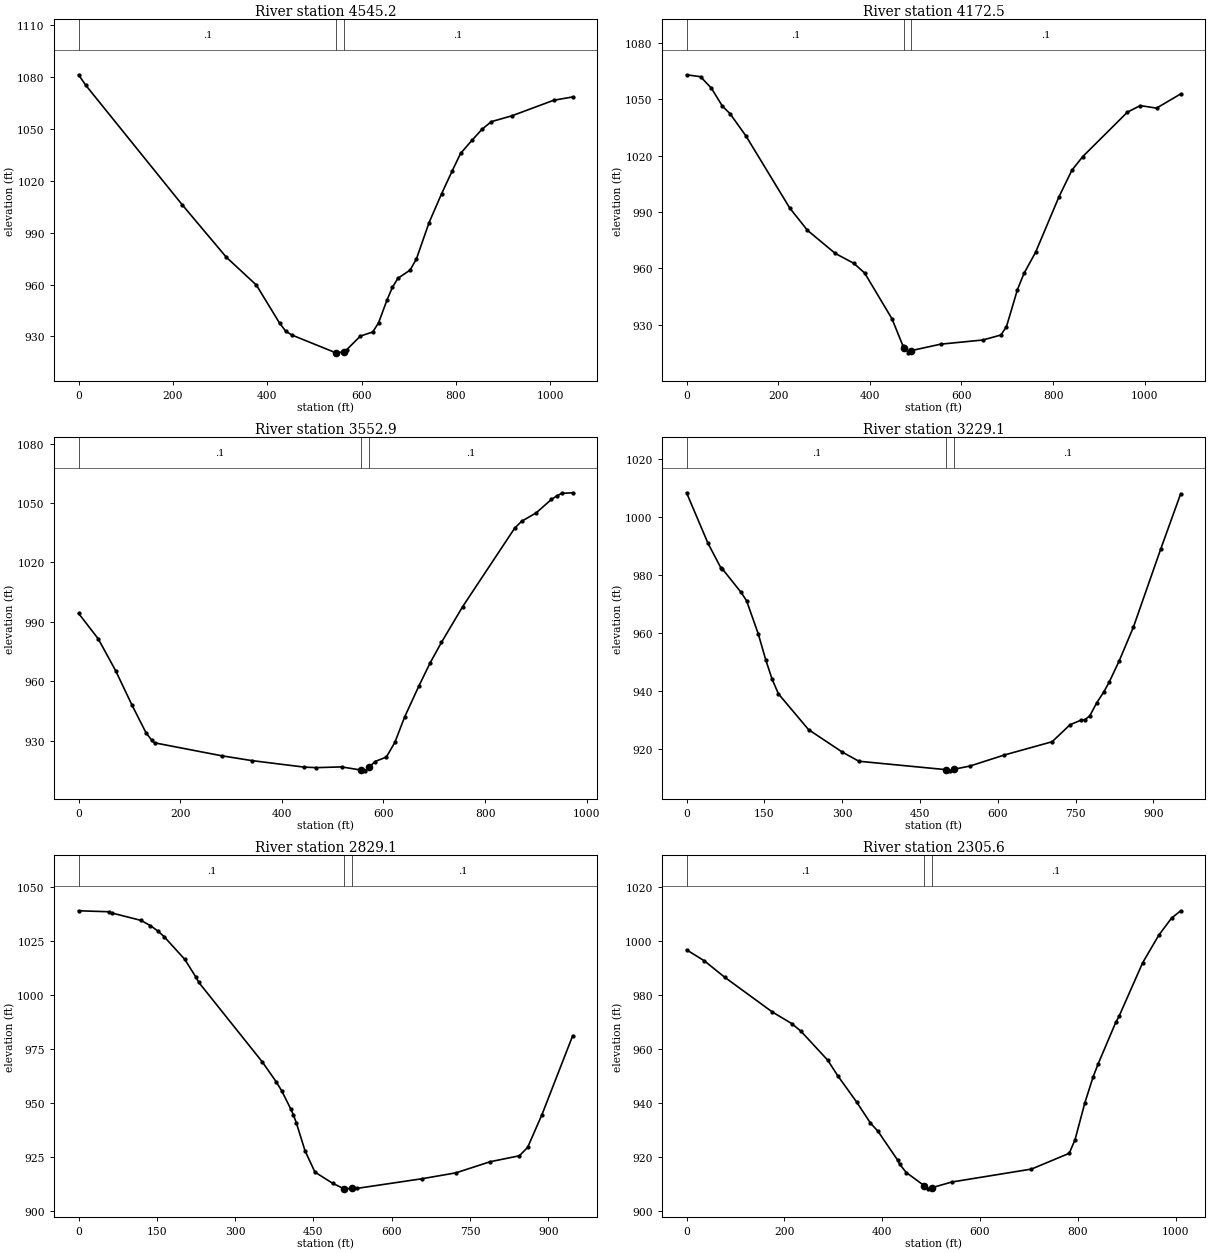
Type RM Length L Ch R = 1 ,4545.2,379.381,372.725,363.68
XS GIS Cut Line= 3
     1743743.554      321819.206     1743527.990      322333.334
     1743301.089      322767.569
#Sta/Elev= 30
       0 1081.37    15.4 1075.27   220.3 1005.98   313.1  975.87   377.0  959.70
   426.4  937.57   439.6  932.90   453.1  930.72   545.4  920.52   546.7  920.57
   561.7  921.10   568.8  922.45   597.4  930.23   623.5  932.58   635.8  937.83
   653.9  951.14   665.3  958.47   677.1  963.69   702.7  968.37   716.1  974.80
   742.9  995.82   769.7 1012.68   792.2 1025.89   809.8 1035.89   834.1 1043.53
   855.5 1049.93   875.0 1054.26   918.3 1057.62  1007.1 1066.63  1047.4 1068.55
#Mann= 3 , 0 , 0
       0     0.1       0   546.7   0.045       0   561.7     0.1       0
Bank Sta=   546.7,   561.7
Exp/Cntr=0.3,0.1

Type RM Length L Ch R = 1 ,4172.5,637.686,619.581,600.152
XS GIS Cut Line= 3
     1743286.062      321671.894     1743233.950      322163.101
     1743197.380      322746.618
#Sta/Elev= 30
       0 1062.99    30.5 1061.96    54.0 1055.91    78.2 1046.30    94.8 1042.31
   129.6 1030.42   225.3  992.02   263.9  980.20   324.5  967.91   364.8  962.67
   388.7  957.47   448.4  933.09   472.2  918.73   475.6  917.68   484.2  914.98
   490.6  916.17   554.5  919.59   646.9  921.82   686.1  924.47   698.3  928.95
   722.1  948.53   736.4  957.23   761.7  968.44   812.7  997.95   841.1 1012.20
   864.9 1019.48   962.3 1043.11   990.4 1046.59  1025.8 1045.23  1078.6 1052.81
#Mann= 3 , 0 , 0
       0     0.1       0   475.6   0.045       0   490.6     0.1       0
Bank Sta=   475.6,   490.6
Exp/Cntr=0.3,0.1

Type RM Length L Ch R = 1 ,3552.9,313.669,323.815,332.221
XS GIS Cut Line= 3
     1742481.041      321947.182     1742837.770      322382.857
     1743122.525      322676.897
#Sta/Elev= 30
       0  994.27    38.6  981.44    72.9  965.32   105.1  947.93   132.6  933.98
   143.7  930.23   149.5  928.84   282.3  922.26   340.9  919.86   443.9  916.56
   467.9  916.30   517.7  916.67   556.4  915.05   562.9  914.68   571.4  916.47
   583.4  919.37   605.7  921.66   622.4  929.02   641.8  941.99   669.5  957.44
   691.8  969.21   714.0  979.54   755.9  997.68   858.4 1037.38   871.7 1040.74
   900.8 1045.10   930.5 1051.85   940.7 1053.56   950.7 1054.89   972.4 1055.20
#Mann= 3 , 0 , 0
       0     0.1       0   556.4   0.045       0   571.4     0.1       0
Bank Sta=   556.4,   571.4
Exp/Cntr=0.3,0.1

Type RM Length L Ch R = 1 ,3229.1,417.357,400,385.379
XS GIS Cut Line= 3
     1742391.941      321934.788     1742523.138      322425.698
     1742704.678      322831.655
#Sta/Elev= 30
       0 1008.20    41.4  990.76    66.5  982.21    68.7  982.05   105.1  973.90
   115.7  971.01   138.4  959.50   152.5  950.75   164.8  944.04   177.1  938.94
   235.3  926.60   300.0  918.91   332.3  915.72   500.6  912.82   508.1  912.42
   515.6  912.98   546.0  914.05   611.9  917.83   704.9  922.45   739.3  928.28
   760.9  929.91   767.6  930.00   777.4  931.33   791.1  935.94   804.0  939.44
   814.9  942.99   834.1  950.26   861.5  961.88   914.1  988.74   952.8 1007.89
#Mann= 3 , 0 , 0
       0     0.1       0   500.6   0.045       0   515.6     0.1       0
Bank Sta=   500.6,   515.6
Exp/Cntr=0.3,0.1

Type RM Length L Ch R = 1 ,2829.1,538.997,523.514,510.52
XS GIS Cut Line= 3
     1741843.388      322363.155     1742282.216      322636.534
     1742655.156      322850.226
#Sta/Elev= 30
       0 1039.15    58.4 1038.70    63.6 1038.13   119.7 1034.68   137.7 1032.24
   152.5 1029.66   164.6 1026.98   203.7 1016.54   224.6 1008.45   230.2 1005.96
   352.2  968.96   378.5  959.85   389.1  955.64   406.5  947.20   411.6  944.41
   417.1  940.86   434.0  927.70   452.9  917.87   487.1  912.62   509.0  910.09
   509.5  910.10   524.5  910.27   533.7  910.31   658.9  914.81   723.1  917.52
   788.8  922.68   844.8  925.44   860.5  929.36   887.8  944.47   946.8  981.16
#Mann= 3 , 0 , 0
       0     0.1       0   509.5   0.045       0   524.5     0.1       0
Bank Sta=   509.5,   524.5
Exp/Cntr=0.3,0.1

Type RM Length L Ch R = 1 ,2305.6,280.826,276.486,269.33
XS GIS Cut Line= 3
     1741782.445      323155.053     1742255.880      323066.887
     1742784.286      323047.786
#Sta/Elev= 30
       0  996.70    36.3  992.63    78.4  986.48   175.4  973.65   214.8  969.38
   233.6  966.56   288.5  955.80   309.1  950.00   347.8  940.24   375.9  932.48
   391.5  929.36   431.8  918.65   435.7  917.20   449.2  914.11   486.2  909.19
   493.5  908.06   501.2  908.46   541.9  910.58   705.2  915.39   782.5  921.25
   794.3  926.33   814.3  939.95   831.3  949.63   841.7  954.49   877.4  969.76
   884.2  972.05   932.7  991.98   965.4 1002.12   991.5 1008.46  1010.3 1011.19
#Mann= 3 , 0 , 0
       0     0.1       0   486.2   0.045       0   501.2     0.1       0
Bank Sta=   486.2,   501.2
Exp/Cntr=0.3,0.1

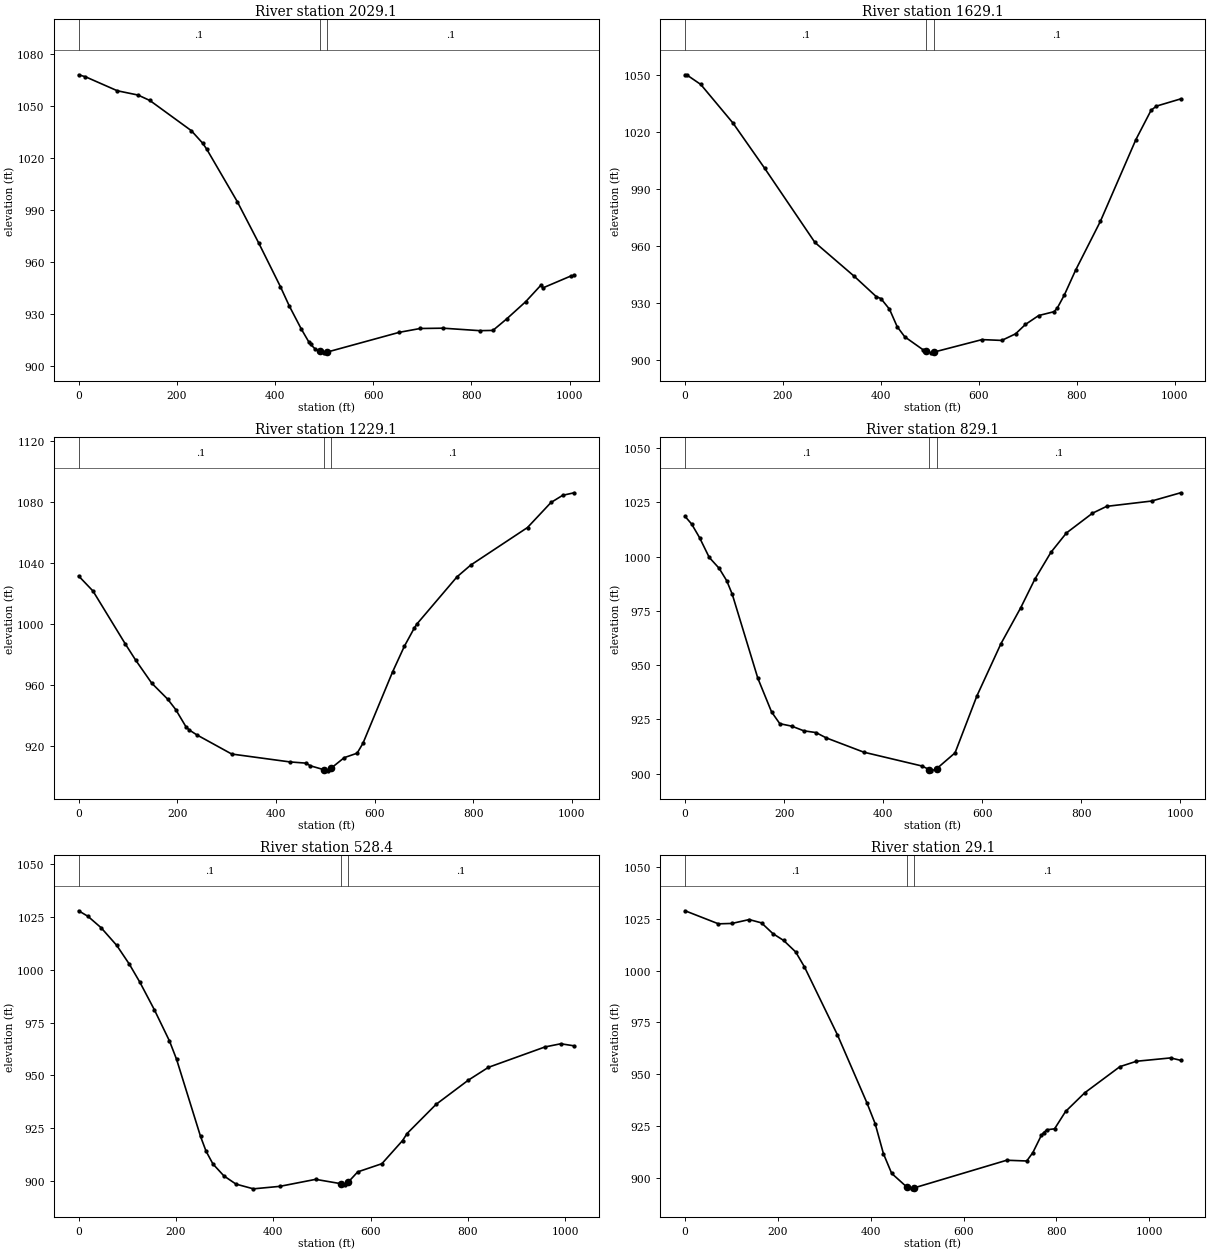
Type RM Length L Ch R = 1 ,2029.1,405.848,400,391.708
XS GIS Cut Line= 3
     1741846.738      323482.327     1742323.612      323336.414
     1742803.629      323162.025
#Sta/Elev= 30
       0 1068.23    13.9 1067.08    78.8 1058.99   120.9 1056.52   145.1 1053.37
   229.5 1035.94   252.6 1028.71   261.1 1025.15   323.3  994.84   367.0  970.90
   411.0  945.77   429.2  934.54   453.6  921.26   469.0  913.75   472.6  912.36
   481.5  909.85   491.2  908.33   500.4  907.51   506.2  907.95   653.0  919.36
   695.7  921.58   742.4  921.76   816.8  920.33   843.9  920.47   871.7  927.07
   910.6  937.07   941.6  946.60   945.8  945.06  1002.8  951.94  1009.4  952.24
#Mann= 3 , 0 , 0
       0     0.1       0   491.2   0.045       0   506.2     0.1       0
Bank Sta=   491.2,   506.2
Exp/Cntr=0.3,0.1

Type RM Length L Ch R = 1 ,1629.1,388.517,400,418.322
XS GIS Cut Line= 3
     1742105.119      323937.878     1742530.701      323675.257
     1742918.428      323340.267
#Sta/Elev= 30
       0 1050.02     4.3 1049.80    32.0 1044.93    97.9 1024.58   162.4 1000.84
   265.3  961.70   346.0  943.81   390.8  933.14   400.0  932.18   417.6  926.58
   433.3  917.37   448.8  912.02   486.9  905.07   492.6  904.54   503.1  903.58
   507.6  903.92   606.7  910.55   647.0  910.12   675.3  913.60   695.4  918.54
   722.4  923.22   753.8  925.25   760.4  927.13   775.0  934.10   797.7  947.01
   848.5  972.83   921.1 1015.91   952.2 1031.37   963.1 1033.52  1012.5 1037.31
#Mann= 3 , 0 , 0
       0     0.1       0   492.6   0.045       0   507.6     0.1       0
Bank Sta=   492.6,   507.6
Exp/Cntr=0.3,0.1

Type RM Length L Ch R = 1 ,1229.1,388.191,400,408.575
XS GIS Cut Line= 3
     1742135.631      324038.499     1742638.534      324006.028
     1743137.573      324045.159
#Sta/Elev= 30
       0 1031.40    29.1 1021.56    94.9  986.78   115.5  976.39   148.2  961.25
   180.6  950.76   196.8  944.00   217.8  932.59   224.7  930.52   239.4  927.46
   310.3  914.88   428.2  909.72   460.8  908.92   469.6  907.20   496.5  904.68
   505.0  903.88   511.5  905.54   538.5  912.53   564.5  915.42   576.4  921.94
   636.5  968.70   660.2  985.36   680.5  997.39   685.9 1000.06   767.0 1030.84
   794.6 1038.49   909.9 1063.12   957.5 1079.50   981.3 1084.22  1004.5 1085.86
#Mann= 3 , 0 , 0
       0     0.1       0   496.5   0.045       0   511.5     0.1       0
Bank Sta=   496.5,   511.5
Exp/Cntr=0.3,0.1

Type RM Length L Ch R = 1 ,829.1,302.448,300.735,298.896
XS GIS Cut Line= 3
     1742102.944      324168.276     1742551.906      324389.487
     1743000.867      324610.698
#Sta/Elev= 30
       0 1018.51    13.2 1015.02    29.1 1008.79    48.7  999.65    68.8  994.60
    84.1  988.88    95.3  982.62   147.0  943.89   174.7  928.40   191.3  923.00
   215.6  921.84   239.9  919.70   264.4  918.90   285.0  916.46   361.0  909.86
   478.4  903.49     493  901.85   497.4  901.26     508  902.21   545.3  909.55
   589.5  935.82   637.9  959.81   678.2  976.53   706.2  989.46   739.0 1001.98
   770.3 1010.90   822.9 1020.00   851.5 1023.16   942.3 1025.61  1001.0 1029.42
#Mann= 3 , 0 , 0
       0     0.1       0     493   0.045       0     508     0.1       0
Bank Sta=     493,     508
Exp/Cntr=0.3,0.1

Type RM Length L Ch R = 1 ,528.4,516.022,499.265,493.402
XS GIS Cut Line= 3
     1741955.650      324472.088     1742460.161      324673.273
     1742902.768      324846.602
#Sta/Elev= 30
       0 1027.78    19.2 1025.15    46.1 1019.80    78.3 1011.44   104.2 1002.58
   126.0  993.99   155.6  981.07   186.7  966.31   201.3  957.64   250.6  921.20
   261.9  914.26   276.1  908.20   298.7  902.57   323.4  898.72   359.2  896.48
   413.4  897.65   487.1  900.96   539.3  898.90   548.4  898.28   554.3  899.70
   573.6  904.48   623.3  908.35   665.8  919.28   675.1  922.61   734.6  936.36
   800.9  947.79   842.2  953.85   958.5  963.48   991.0  964.98  1018.5  964.00
#Mann= 3 , 0 , 0
       0     0.1       0   539.3   0.045       0   554.3     0.1       0
Bank Sta=   539.3,   554.3
Exp/Cntr=0.3,0.1

Type RM Length L Ch R = 1 ,29.1,29.126,29.126,17.145
XS GIS Cut Line= 3
     1741833.322      325218.693     1742270.735      325006.317
     1742851.614      325027.977
#Sta/Elev= 30
       0 1028.85    71.9 1022.55   100.9 1022.74   138.1 1024.61   164.6 1023.01
   189.0 1017.85   212.4 1014.51   238.2 1008.99   257.1 1001.78   328.3  968.92
   391.7  936.17   409.5  926.07   427.3  911.61   445.0  902.14   478.7  895.33
   488.8  894.68   493.7  895.16   692.8  908.48   736.0  908.12   749.1  912.16
   767.5  920.52   772.2  921.74   779.2  923.19   795.9  923.63   819.7  932.03
   860.9  941.02   936.7  953.64   972.4  956.24  1045.8  957.85  1067.5  956.70
#Mann= 3 , 0 , 0
       0     0.1       0   478.7   0.045       0   493.7     0.1       0
Bank Sta=   478.7,   493.7
Exp/Cntr=0.3,0.1